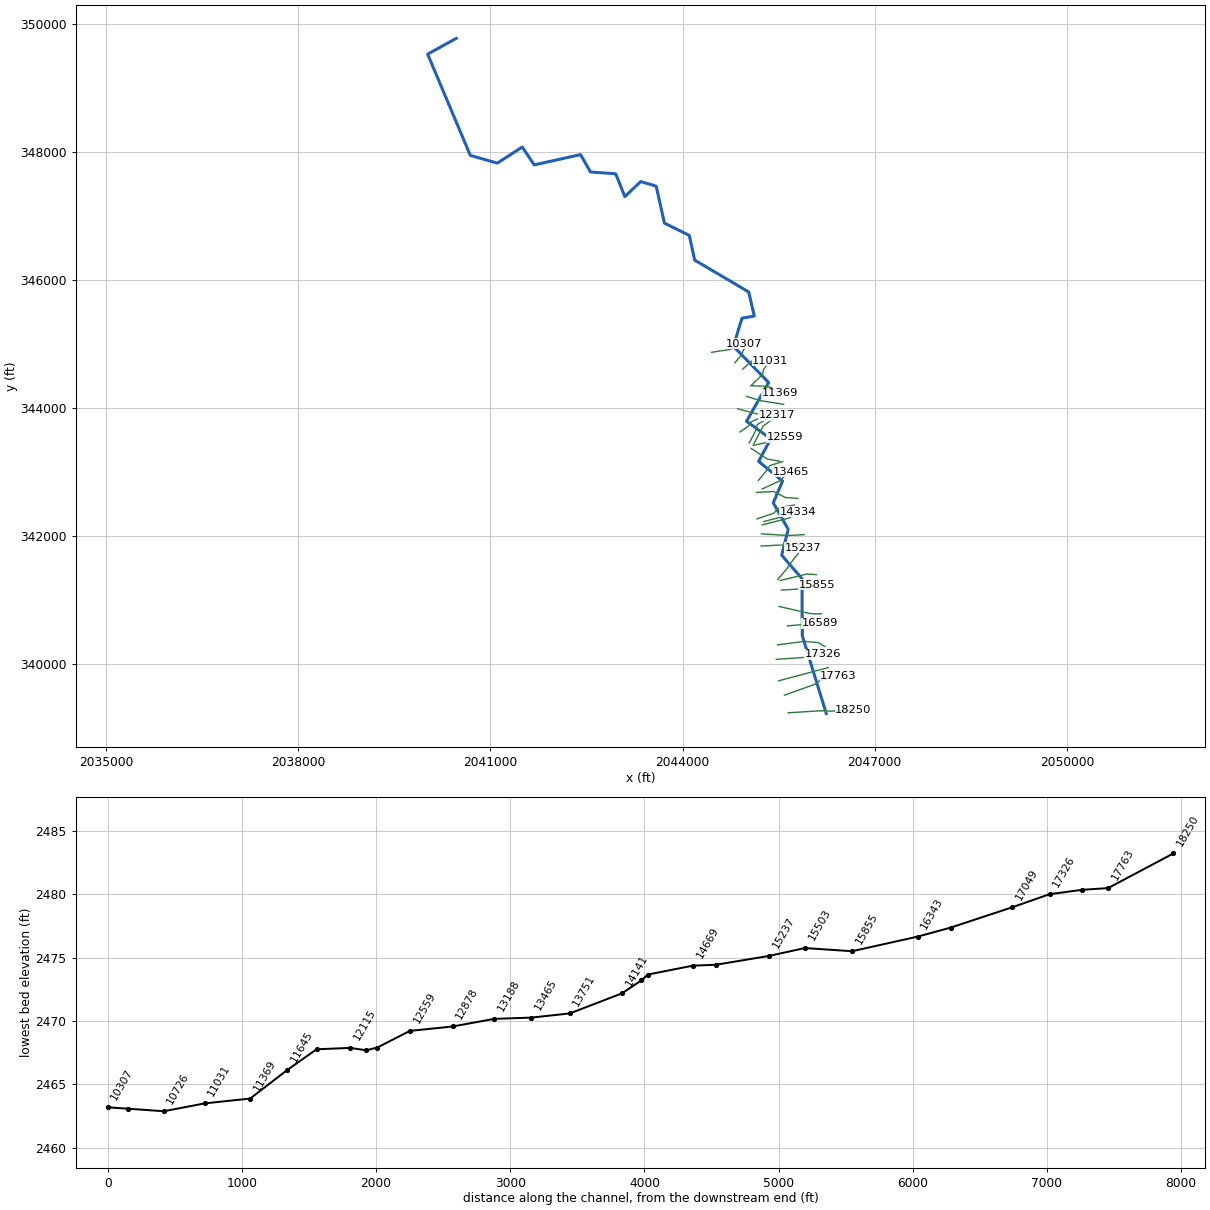
--- LTSEWELLCK.prj (project) ---

Proj Title=LTSEWELLCK
Current Plan=p01
Default Exp/Contr=0,0
English Units
Geom File=g01
Flow File=f01
Plan File=p01
BEGIN DESCRIPTION:
Stream Name- Little Sewell Creek
Flood Zone: Zone A
Greenbrier County, WV
County-Wide Study
WVDHSEM-2018-3, Flood Risk Project
HEC-RAS Version: 5.0.7
General Notes:
For the Hydrology Regression was used.
END DESCRIPTION:
DSS File=dss
DSS Export Rating Curves= 0
DSS Export Rating Curve Sorted= 0
DSS Export Volume Flow Curves= 0
DXF OffsetX= 0
DXF OffsetY= 0
DXF ScaleX= 0
DXF ScaleY= 0

--- LTSEWELLCK.p01 (plan) ---

Plan Title=Floodplain
Program Version=5.07
Short Identifier=Floodplain
Geom File=g01
Flow File=f01
Subcritical Flow
K Sum by GR= 0
Std Step Tol= 0.01
Critical Tol= 0.01
Num of Std Step Trials= 20
Max Error Tol= 0.3
Flow Tol Ratio= 0.001
Split Flow NTrial= 30
Split Flow Tol= 0.02
Split Flow Ratio= 0.02
Log Output Level= 0
Friction Slope Method= 1
Unsteady Friction Slope Method= 2
Unsteady Bridges Friction Slope Method= 1
Parabolic Critical Depth
Global Vel Dist= 0 , 0 , 0
Global Log Level= 0
CheckData=False
Encroach Param=-1 ,0,0, 0
Computation Interval=0.1SEC
Output Interval=1MIN
Instantaneous Interval=Max Profile
Mapping Interval=1HOUR
Computation Time Step Use Courant=        0
Computation Time Step Use Time Series=    0
Computation Time Step Count To Double=0
Computation Time Step Max Doubling=0
Computation Time Step Max Halving=0
Computation Time Step Residence Courant=0
Run HTab= 0
Run UNet= 0
Run Sediment= 0
Run PostProcess= 0
Run WQNet= 0
Run RASMapper= 0
UNET Theta= 0
UNET Theta Warmup= 0
UNET ZTol= 0
UNET ZSATol= 0
UNET MxIter= 0
UNET Max Iter WO Improvement= 0
UNET MaxInSteps= 0
UNET DtIC= 0
UNET DtMin= 0
UNET MaxCRTS= 0
UNET WFStab= 0
UNET SFStab= 0
UNET WFX= 1
UNET SFX= 1
UNET 1D Methodology=Finite Difference
UNET DSS MLevel= 1
UNET Pardiso=0
UNET DZMax Abort= 0
UNET Use Existing IB Tables= 0
UNET Froude Reduction=False
UNET Froude Limit= 0
UNET Froude Power= 0
UNET D1 Cores= 0
UNET D2 Coriolis=0
UNET D2 Cores= 0
UNET D2 Theta= 1
UNET D2 Theta Warmup= 1
UNET D2 Z Tol= 0.01
UNET D2 Volume Tol= 0.01
UNET D2 Max Iterations= 20
UNET D2 Equation= 0
UNET D2 RampUpFraction=0.1
UNET D2 TimeSlices= 1
UNET D2 BCVolumeCheck=0
UNET D1D2 MaxIter= 0
UNET D1D2 ZTol=0.01
UNET D1D2 QTol=0.1
UNET D1D2 MinQTol=1
DSS File=dss
Write IC File= 0
Write IC File at Fixed DateTime=0
Write IC File at Sim End=0
Echo Input=False
Echo Parameters=False
Echo Output=False
Write Detailed= 0
HDF Write Warmup=0
HDF Write Time Slices=0
HDF Flush=0
HDF Face Node Velocities=0
HDF Compression= 1
HDF Chunk Size= 1
HDF Spatial Parts= 1
HDF Use Max Rows=0
HDF Fixed Rows= 1
Calibration Method= 0
Calibration Iterations= 20
Calibration Max Change=0.05
Calibration Tolerance=0.2
Calibration Maximum=1.5
Calibration Minimum=0.5
Calibration Optimization Method= 1
WQ AD Non Conservative
WQ ULTIMATE=-1
WQ Max Comp Step=1HOUR
WQ Output Interval=15MIN
WQ Output Selected Increments= 0
WQ Output face flow=0
WQ Output face velocity=0
WQ Output face area=0
WQ Output face dispersion=0
WQ Output cell volume=0
WQ Output cell surface area=0
WQ Output cell continuity=0
WQ Output cumulative cell continuity=0
WQ Output face conc=0
WQ Output face dconc_dx=0
WQ Output face courant=0
WQ Output face peclet=0
WQ Output face adv mass=0
WQ Output face disp mass=0
WQ Output cell mass=0
WQ Output cell source sink temp=0
WQ Output nsm pathways=0
WQ Output nsm derived pathways=0
WQ Output MaxMinRange=-1
WQ Daily Max Min Mean=-1
WQ Daily Range=0
WQ Daily Time=0
WQ Create Restart=0
WQ Fixed Restart=0
WQ System Summary=0
WQ Write To DSS=0
WQ Use Fixed Temperature=0
Sorting and Armoring Iterations= 10
XS Update Threshold= 0.02
Bed Roughness Predictor= 0
Hydraulics Update Threshold= 0.02
Energy Slope Method= 1
Volume Change Method= 0
Sediment Retention Method= 0
XS Weighting Method= 0
Number of US Weighted Cross Sections= 1
Number of DS Weighted Cross Sections= 1
Upstream XS Weight=0.25
Main XS Weight=0.5
Downstream XS Weight=0.25
Number of DS XS's Weighted with US Boundary= 1
Upstream Boundary Weight= 1
Weight of XSs Associated with US Boundary= 0
Number of US XS's Weighted with DS Boundary= 1
Downstream Boundary Weight= 0.5
Weight of XSs Associated with DS Boundary= 0.5
Percentile Method= 0
Sediment Output Level= 4
Mass or Volume Output= 0
Output Increment Type= 1
Profile and TS Output Increment= 10
XS Output Flag= 0
XS Output Increment= 10
Write Gradation File= 0
Read Gradation Hotstart= 0
Write HDF5 File= 1
Write Binary Output= 1
Write DSS Sediment File= 0
SV Curve= 0
Specific Gage Flag= 0

--- LTSEWELLCK.f01 (steady flow) ---

Flow Title=Multiprofile
Program Version=5.07
BEGIN FILE DESCRIPTION:
Additional flow file from Sewell Creek Junction Model added to xs 767 for a smooth tie in. Known WS enforced at the most ds xs
END FILE DESCRIPTION:
Number of Profiles= 6
Profile Names=f1p,f10p,f4p,f2p,f02p,f1pplus
River Rch & RM=LTSEWELLCK,Main            ,18250
     548     289     385     463     766     810
River Rch & RM=LTSEWELLCK,Main            ,16589
     633     336     446     537     883     937
River Rch & RM=LTSEWELLCK,Main            ,13751
     801     429     567     680    1110    1190
River Rch & RM=LTSEWELLCK,Main            ,11645
     914     492     649     777    1270    1350
River Rch & RM=LTSEWELLCK,Main            ,7028
    1100     595     781     934    1510    1620
River Rch & RM=LTSEWELLCK,Main            ,1645
    2630    1480    1910    2260    3570    3890
River Rch & RM=LTSEWELLCK,Main            ,767
    2811    1580    2039    2413    3811    4157
Boundary for River Rch & Prof#=LTSEWELLCK,Main            , 1
Up Type= 0
Dn Type= 1
Dn Known WS=2404
Boundary for River Rch & Prof#=LTSEWELLCK,Main            , 2
Up Type= 0
Dn Type= 1
Dn Known WS=2400.47
Boundary for River Rch & Prof#=LTSEWELLCK,Main            , 3
Up Type= 0
Dn Type= 1
Dn Known WS=2402.39
Boundary for River Rch & Prof#=LTSEWELLCK,Main            , 4
Up Type= 0
Dn Type= 1
Dn Known WS=2402.82
Boundary for River Rch & Prof#=LTSEWELLCK,Main            , 5
Up Type= 0
Dn Type= 1
Dn Known WS=2406.3
Boundary for River Rch & Prof#=LTSEWELLCK,Main            , 6
Up Type= 0
Dn Type= 1
Dn Known WS=2406.81
DSS Import GetInterval= 0
DSS Import GetPeak= 0
DSS Import FillOption= 0

--- LTSEWELLCK.g01 (geometry) ---

Geom Title=West Virginia 2016 QL2 LiDAR Project
Program Version=5.07

River Reach=LTSEWELLCK      ,Main
Reach XY= 30
2046242.22400004 339231.65200001 2045869.0322502340446.283350527
2045864.17113909341335.8666838562045547.47169492341702.523111701
2045649.58780575342106.700017199 2045416.2544724342519.894461647
2045560.69891685342859.4777950052045187.29205418343167.933677271
2045376.67113909343519.8944616622044998.19891685343794.200017229
2045343.33780572344399.0611283482044794.03225017 344965.72779502
2044927.36558351 345403.227795022045120.42113906345437.950017244
2045032.22669461345814.3389061392044189.86558348346310.866683915
2044105.83780572346696.9777950352043717.64336127346889.338906154
2043588.47669458347466.4222394972043346.81002796347537.950017273
2043100.28225014347303.2277950352042957.22669458 347659.47779505
2042563.47669458347687.2555728262042407.92113906347959.477795064
2041684.31002793347797.6722395122041498.89336124348077.533350602
2041109.31002793347825.4500172882040687.78225011347946.283350617
 2040021.8100279349528.2277950792040468.68417242349774.980558604

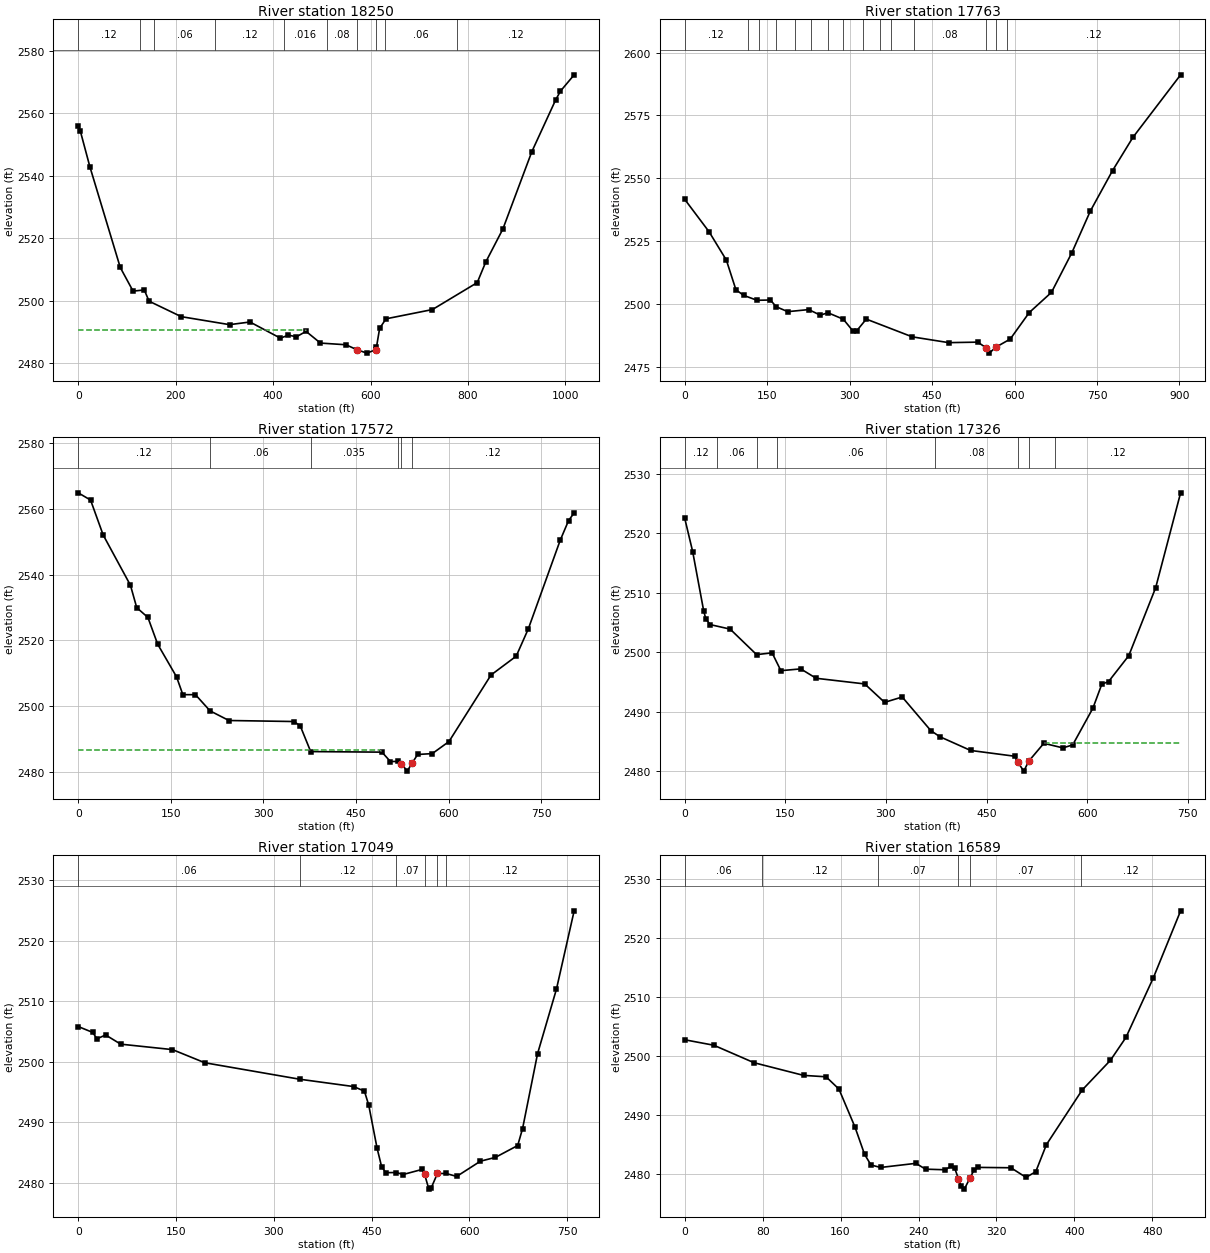
Type RM Length L Ch R = 1 ,18250   ,436.7,487.3,492.3
XS GIS Cut Line= 4
     2045650.884      339241.156     2046157.002      339272.527
     2046318.039      339266.253     2046667.302      339280.892
#Sta/Elev= 30
       0 2555.85     4.1  2554.5    23.8    2543    86.3 2510.66   112.6 2503.09
   135.6 2503.47   145.4 2499.87   211.5 2494.91   310.6 2492.35   352.5  2493.2
     415 2488.02   431.4    2489   447.8 2488.46   467.6  2490.2   497.1 2486.45
   549.5 2485.91   571.62484.353   592.4 2483.23   610.22484.296   612.1 2485.14
   618.6 2491.17   631.7 2494.22     727 2497.19   818.9 2505.82   836.4 2512.42
   871.5 2522.98   930.9 2547.74   979.8 2564.33   989.7 2567.15  1017.8 2572.37
#Mann= 10 ,-1 , 0
       0     .12       0   125.9    .016       0  155.49     .06       0
  280.72     .12       0  421.84    .016       0  510.61     .08       0
   571.6     .04       0   610.2     .08       0  628.85     .06       0
  776.66     .12       0
#XS Ineff= 2 , 0
          467.24 2490.55
Permanent Ineff=
       F       F
Bank Sta=571.6,610.2
XS Rating Curve= 0 ,0
Exp/Cntr=0.3,0.1

Type RM Length L Ch R = 1 ,17763   ,199.6,191.1,183.2
XS GIS Cut Line= 4
     2045590.234      339515.129     2046083.803      339692.897
     2046142.362      339743.091     2046435.158      339810.015
#Sta/Elev= 30
       0 2541.66    44.4 2528.74    75.8 2517.48    93.2  2505.7   107.1 2503.47
   131.6  2501.5     156 2501.61   166.4 2498.95   187.4 2496.98   225.7  2497.8
   246.6 2495.59   260.6 2496.54   288.5 2493.98   305.9 2489.34   312.9 2489.37
   330.3 2494.02     414 2486.96   480.2 2484.66   533.2 2484.86   547.62482.713
   554.2 2480.49   565.8 2482.82   592.2 2486.09   626.8 2496.63   667.2 2504.66
   704.2 2520.38   737.8 2536.95   778.2 2553.04   815.2 2566.25   902.1 2591.15
#Mann= 15 ,-1 , 0
       0     .12       0  114.39     .06       0  135.23    .016       0
  166.62     .12       0  201.56     .06       0  229.41     .12       0
  260.81     .06       0  288.73     .12       0  323.59     .06       0
  354.99     .12       0   375.9     .06       0  417.78     .08       0
   547.6     .04       0   565.8     .08       0  586.74     .12       0
Bank Sta=547.6,565.8
XS Rating Curve= 0 ,0
Exp/Cntr=0.3,0.1

Type RM Length L Ch R = 1 ,17572   ,248,245.1,242.8
XS GIS Cut Line= 2
 2045497.7938053339739.4266984472046273.88202716339946.985176386
#Sta/Elev= 30
       0  2564.8      20 2562.61    40.4 2552.02    84.6 2536.76    94.8 2529.96
   112.9 2526.99   128.7 2518.88   159.3 2508.96   169.5 2503.56   189.9 2503.56
   213.6 2498.64   244.2 2495.72   349.5 2495.41   359.7 2494.08   376.6 2486.29
   492.1 2486.12   505.7 2483.27   517.7 2483.31   523.6 2482.62   532.9 2480.36
   540.72482.722   549.8 2485.41   573.6 2485.68   600.6 2489.33   668.7 2509.52
   709.5 2515.23   729.2 2523.55   780.8  2550.4   794.4  2556.4   803.4 2558.71
#Mann= 6 ,-1 , 0
       0     .12       0   213.6     .06       0   376.6    .035       0
   517.7     .06       0   523.6     .04       0   540.7     .12       0
#XS Ineff= 2 , 0
           491.3 2486.73
Permanent Ineff=
       F       F
Bank Sta=523.6,540.7
XS Rating Curve= 0 ,0
Exp/Cntr(USF)=0,0
Exp/Cntr=0.3,0.1

Type RM Length L Ch R = 1 ,17326   ,250,277.2,239.4
XS GIS Cut Line= 4
     2045462.659      340075.623     2045887.212      340104.902
     2046037.792      340123.725     2046196.738      340155.096
#Sta/Elev= 30
       0 2522.58    11.9 2516.95    28.3 2506.99    31.6 2505.58    38.1 2504.66
    67.8  2503.9   107.2 2499.61   130.3 2499.91   143.4 2496.91     173 2497.21
     196 2495.63   268.4 2494.68     298 2491.58   324.3 2492.48   366.8 2486.84
   380.2 2485.81   426.2 2483.49   492.4 2482.51   496.62481.496   505.6 2480.01
   512.72481.658   535.4 2484.69   563.8 2483.92   578.4 2484.42   608.5 2490.59
   621.8 2494.63   631.9 2495.08     662 2499.43   702.1 2510.87   739.3 2526.83
#Mann= 8 ,-1 , 0
       0     .12       0   48.15     .06       0  107.36    .016       0
  136.97     .06       0  373.83     .08       0   496.6     .04       0
   512.7     .07       0  552.15     .12       0
#XS Ineff= 2 , 0
                          536.35         2484.71
Permanent Ineff=
       F       F
Bank Sta=496.6,512.7
XS Rating Curve= 0 ,0
Exp/Cntr=0.3,0.1

Type RM Length L Ch R = 1 ,17049   ,342.6,460.5,291.1
XS GIS Cut Line= 4
2045482.06222843340301.3868528692045902.94779233 340356.40457364
2046117.51690334 340337.14837137 2046222.0505728340276.628878522
#Sta/Elev= 30
       0 2505.82    22.2 2504.85    28.8 2503.79      42 2504.43    65.2 2502.91
   144.6 2502.01   194.2 2499.84   339.8 2497.12   422.5 2495.91     439 2495.15
   445.6 2492.85   458.4 2485.75   465.4 2482.67   471.9  2481.7   488.1 2481.72
   498.3 2481.39     528 2482.25   531.2 2481.48   537.8 2478.98   541.1  2479.1
     551 2481.56   564.2 2481.56   580.6 2481.08   616.9 2483.59   639.9 2484.22
   674.1 2486.18   681.6 2488.98   704.6 2501.35   733.5 2511.97   760.7 2524.92
#Mann= 6 ,-1 , 0
       0     .06       0   339.8     .12       0   488.1     .07       0
   531.2     .04       0     551     .07       0   564.2     .12       0
Bank Sta=531.2,551
XS Rating Curve= 0 ,0
Exp/Cntr(USF)=0,0
Exp/Cntr=0.3,0.1

Type RM Length L Ch R = 1 ,16589   ,195.5,246,188.6
XS GIS Cut Line= 4
     2045638.336      340598.471     2045883.029      340619.385
     2045962.502      340606.837     2046142.362      340640.299
#Sta/Elev= 30
       0 2502.74    29.9 2501.81    71.2 2498.84     122 2496.69   145.1 2496.45
   158.3 2494.37   174.7 2487.95   184.6 2483.29   191.2 2481.47   201.1 2481.05
   237.3 2481.75   247.2 2480.76     267 2480.66   273.8 2481.25   277.1 2480.94
     2812479.123   283.7 2477.87     287 2477.37   292.8 2479.25     297 2480.63
   301.4 2481.06   334.8    2481   350.3 2479.37   360.3 2480.32   371.3 2484.94
   407.9 2494.19     437 2499.26   452.9 2503.14   481.1  2513.3     509 2524.64
#Mann= 6 ,-1 , 0
       0     .06       0    79.4     .12       0  197.98     .07       0
     281     .04       0   292.8     .07       0  407.26     .12       0
Bank Sta=281,292.8
XS Rating Curve= 0 ,0
Exp/Cntr=0.3,0.1

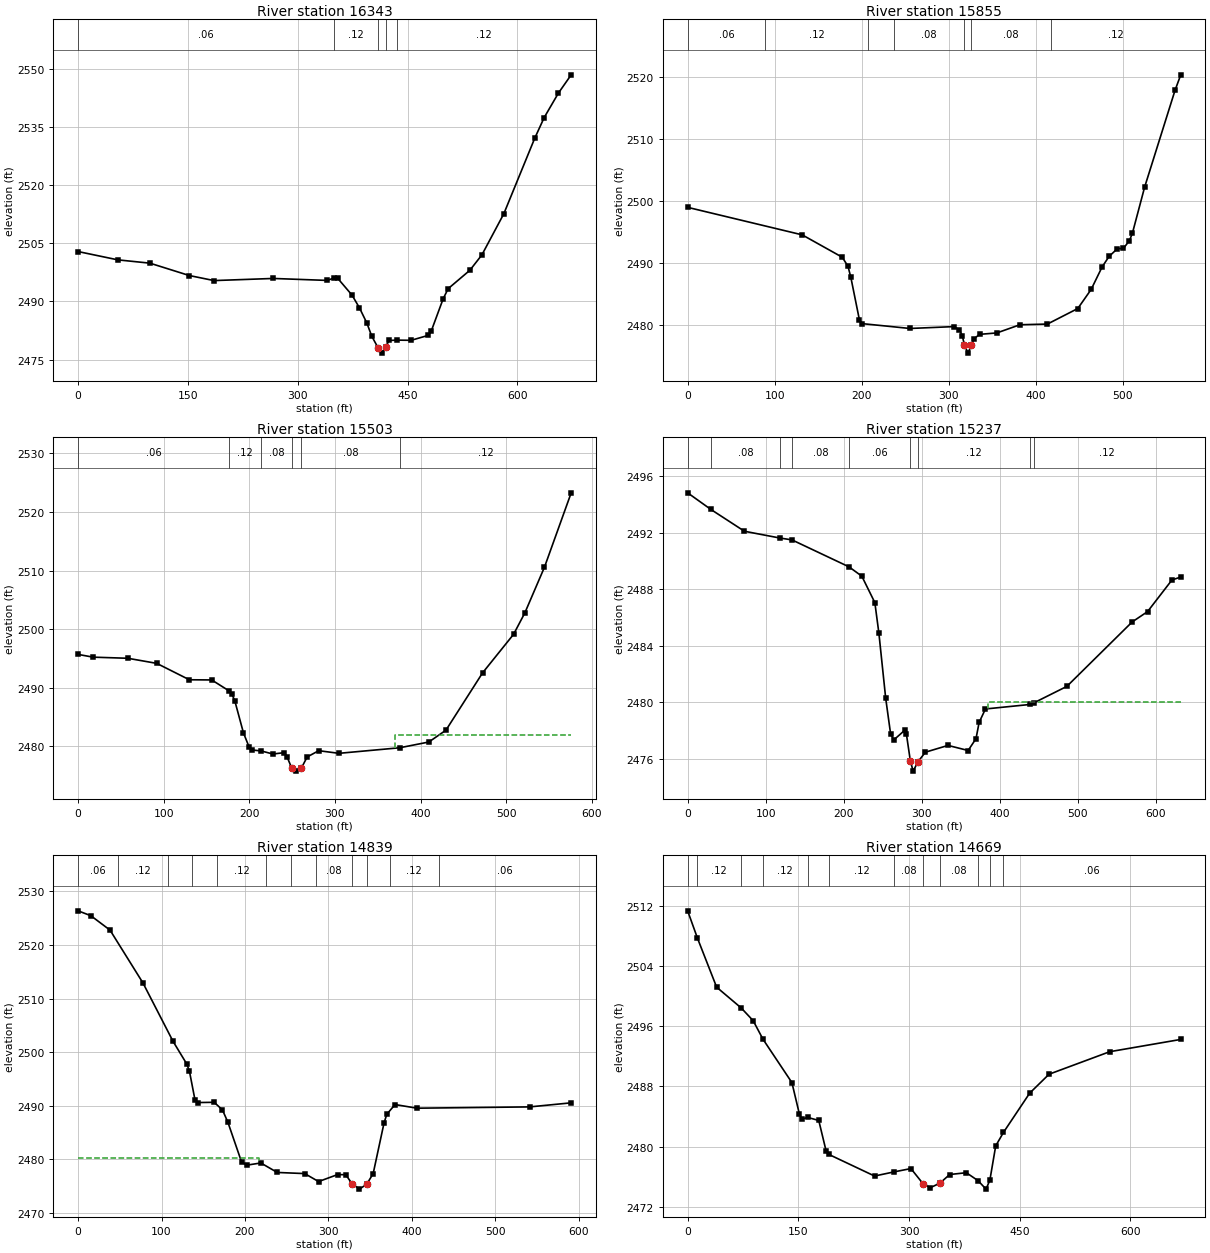
Type RM Length L Ch R = 1 ,16343   ,399.5,488.1,392.2
XS GIS Cut Line= 3
2045506.81808695340901.7541749062046001.34872134340788.048226122
2046167.39550369340786.243369792
#Sta/Elev= 30
       0  2502.9    54.4 2500.75    98.1  2499.9     152  2496.7   185.7  2495.4
   266.5 2495.95   340.5 2495.44   350.2 2496.14   354.6 2495.99   374.2 2491.64
   384.3 2488.36   394.4 2484.44   401.1 2481.04   409.8 2478.01   414.6 2476.66
   420.1 2478.23   424.7 2479.93   435.7 2480.02   454.9 2479.97   478.5 2481.26
   482.3 2482.32   498.7 2490.73   505.5 2493.32   535.1 2498.06   551.5 2502.03
   581.5 2512.67   623.6 2532.12   636.6 2537.51   656.1 2543.85   673.5 2548.55
#Mann= 5 ,-1 , 0
       0     .06       0   350.2     .12       0   409.8     .04       0
   420.1     .08       0   435.7     .12       0
Bank Sta=409.8,420.1
XS Rating Curve= 0 ,0
Exp/Cntr(USF)=0,0
Exp/Cntr=0.3,0.1

Type RM Length L Ch R = 1 ,15855   ,205.7,351.2,239
XS GIS Cut Line= 4
      2045540.04      341156.874     2045807.739      341173.605
     2045910.217      341173.605      2046094.26       341240.53
#Sta/Elev= 30
       0 2499.04   131.6  2494.6   177.6 2490.99   184.2 2489.53   187.5 2487.73
   197.3  2480.9   200.6 2480.27   255.4 2479.49   305.7 2479.79   312.3 2479.27
   315.6 2478.28   317.82476.902   322.1 2475.51   325.92476.817     329 2477.82
   335.3 2478.54   355.2 2478.77   381.7 2480.09   413.3  2480.2   448.2 2482.71
   463.6  2485.8   476.1 2489.41   484.1 2491.11   493.6 2492.36   500.6 2492.41
   507.5 2493.66     511 2494.89     525 2502.31   559.9 2517.92   566.5 2520.43
#Mann= 7 ,-1 , 0
       0     .06       0   88.96     .12       0  207.34     .06       0
  236.93     .08       0   317.8     .04       0   325.9     .08       0
     417     .12       0
Bank Sta=317.8,325.9
XS Rating Curve= 0 ,0
Exp/Cntr=0.3,0.1

Type RM Length L Ch R = 1 ,15503   ,194.6,266.6,257.4
XS GIS Cut Line= 3
2045523.06179392341306.0419928052045941.78846246341408.918803609
2046086.17696885 341398.08966563
#Sta/Elev= 30
       0 2495.69    17.6 2495.22    58.1 2495.03    91.9 2494.16     130 2491.36
   156.1 2491.33   176.4 2489.46   179.7  2488.9   183.1 2487.75   193.2 2482.28
     200  2479.8   203.4 2479.37   214.1  2479.2   227.6 2478.68   240.5 2478.91
     244 2478.24   249.62476.266   254.1 2475.76   260.8 2476.27   267.6 2478.18
   281.1 2479.25   304.7  2478.8   375.7 2479.75   409.7 2480.73   429.7 2482.75
   472.5 2492.54   508.7 2499.12   521.9 2502.79   544.8 2510.59     576 2523.28
#Mann= 6 ,-1 , 0
       0     .06       0   176.4     .12       0   214.1     .08       0
   249.6     .04       0   260.8     .08       0   375.7     .12       0
#XS Ineff= 2 , 0
                             370            2482
Permanent Ineff=
       F       F
Bank Sta=249.6,260.8
XS Rating Curve= 0 ,0
Exp/Cntr(USF)=0,0
Exp/Cntr=0.3,0.1

Type RM Length L Ch R = 1 ,15237   ,376.4,397.5,304.4
XS GIS Cut Line= 4
2045486.41176388341323.3290569072045609.69489775341468.479062496
     2045738.723       341646.26     2045878.637        341818.8
#Sta/Elev= 30
       0 2494.84    29.9 2493.66    72.8 2492.12   118.3 2491.64   133.7 2491.51
   206.9  2489.6   223.3 2488.94     240 2487.07   245.2  2484.9   253.9  2480.3
   260.2 2477.78   264.3 2477.35   278.7 2478.05   280.5 2477.75   285.52475.873
   289.1 2475.14   295.4 2475.81   304.8 2476.48   333.8 2476.96   359.6  2476.6
   369.7 2477.44   373.7 2478.59   381.8 2479.54   439.2 2479.86   443.8 2479.97
   486.2 2481.14   569.9  2485.7   589.6 2486.43   620.9 2488.67   632.2 2488.88
#Mann= 9 ,-1 , 0
       0     .06       0    29.9     .08       0   118.3     .04       0
   133.7     .08       0   206.9     .06       0   285.5     .04       0
   295.4     .12       0   439.2     .06       0   443.8     .12       0
#XS Ineff= 2 , 0
                             385            2480
Permanent Ineff=
       F       F
Bank Sta=285.5,295.4
XS Rating Curve= 0 ,0
Exp/Cntr=0.3,0.1

Type RM Length L Ch R = 1 ,14839   ,157.8,170.6,159.8
XS GIS Cut Line= 4
     2045226.331      341844.943     2045498.213      341859.583
     2045632.062      341861.674     2045816.105      341878.405
#Sta/Elev= 30
       0 2526.36    15.3 2525.45    38.3 2522.76    77.7 2512.92   113.8 2502.01
   130.3 2497.77   133.5  2496.4   140.1 2491.08   143.4 2490.59   163.1 2490.64
     173 2489.22   179.5 2486.93     196 2479.46   202.5 2478.92     219 2479.32
   238.7 2477.55   271.6 2477.34   288.2 2475.85   310.9 2477.15   320.8 2477.13
   328.2 2475.46   337.2 2474.44   345.9 2475.36   353.6 2477.33   366.7 2486.83
     370 2488.41   379.8 2490.22   406.1 2489.54   541.1 2489.78   590.9 2490.54
#Mann= 12 ,-1 , 0
       0     .06       0   48.11     .12       0  107.27     .06       0
  136.85    .016       0  166.43     .12       0  225.59     .06       0
  255.17     .12       0  284.73     .08       0   328.2     .04       0
   345.9     .08       0  373.35     .12       0  432.54     .06       0
#XS Ineff= 2 , 0
          216.52  2480.3
Permanent Ineff=
       F       F
Bank Sta=328.2,345.9
XS Rating Curve= 0 ,0
Exp/Cntr=0.3,0.1

Type RM Length L Ch R = 1 ,14669   ,257.8,334.7,269
XS GIS Cut Line= 4
     2045231.581      342035.698     2045513.668      342017.693
     2045669.716       342010.69     2045898.786      342023.694
#Sta/Elev= 30
       0 2511.33    13.3  2507.7    39.3 2501.19    72.5 2498.44    88.8 2496.74
   102.1 2494.28   141.3 2488.52   151.4 2484.36   154.7 2483.67   162.8 2483.89
   177.7 2483.49   187.5  2479.5   190.9    2479   253.3 2476.11   280.3 2476.67
   302.6  2477.1     319 2475.09   328.9 2474.56     342 2475.17   355.1 2476.31
   377.7 2476.55   393.5  2475.5   404.4 2474.37   409.62475.563   417.5 2480.11
     428  2481.9   463.5 2487.11   489.8 2489.63     572 2492.62   668.3 2494.25
#Mann= 12 ,-1 , 0
       0     .12       0    13.3     .12       0    72.5     .06       0
   102.1     .12       0   162.8    .016       0   190.9     .12       0
   280.3     .08       0     319     .04       0     342     .08       0
   393.5     .04       0   409.6     .12       0     428     .06       0
Bank Sta=319,342
XS Rating Curve= 0 ,0
Exp/Cntr=0.5,0.3

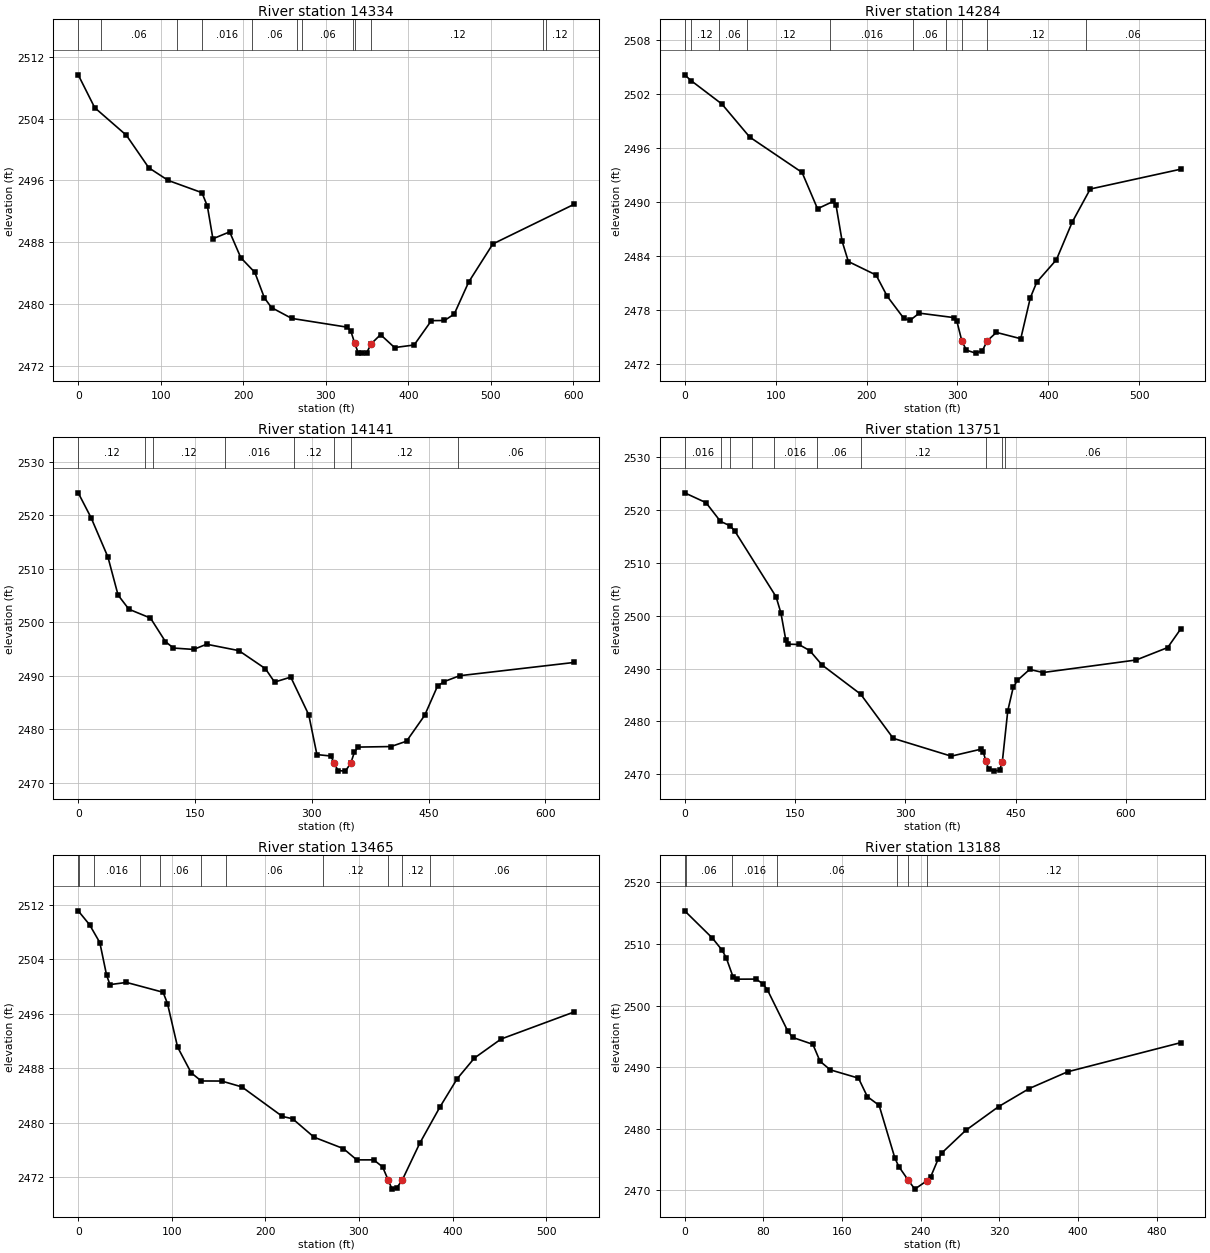
Type RM Length L Ch R = 1 ,14334   ,47.3,50.4,53.6
XS GIS Cut Line= 4
     2045247.245      342177.475     2045544.677      342251.765
     2045658.712      342281.774     2045804.757      342380.804
#Sta/Elev= 30
       0 2509.66      20 2505.41    58.4 2501.84    85.5 2497.64   109.1    2496
   149.9 2494.42   156.5 2492.68   163.2 2488.46   183.5 2489.35     197 2486.01
     214 2484.11   225.6 2480.81   234.2 2479.56   258.7 2478.16   325.7 2477.03
   330.3 2476.54   334.9 2474.98   339.2 2473.72   344.1 2473.67   349.4  2473.7
   355.1 2474.89   366.3 2476.06   383.3 2474.39     407 2474.72   427.9 2477.87
   443.8 2477.89   455.6 2478.72   473.1 2482.86   502.4 2487.79   600.9 2492.92
#Mann= 12 ,-1 , 0
       0     .12       0   27.95     .06       0  119.28     .12       0
  149.73    .016       0  210.62     .06       0  265.33    .016       0
  271.51     .06       0  332.48     .12       0   334.9     .04       0
   355.1     .12       0  563.74     .06       0  566.79     .12       0
Bank Sta=334.9,355.1
XS Rating Curve= 0 ,0
Exp/Cntr=0.5,0.3

Type RM Length L Ch R = 1 ,14284   ,128.5,142.1,154.1
XS GIS Cut Line= 4
     2045267.592      342227.757     2045542.676      342299.779
     2045671.716      342349.795     2045773.748      342417.816
#Sta/Elev= 30
       0  2504.1       7 2503.46    40.9 2500.86    71.5 2497.19   129.1 2493.26
   146.1 2489.23   163.6 2490.06   166.4 2489.65   173.2  2485.6     180 2483.37
   210.5 2481.87   222.7 2479.52     241 2477.06   247.8 2476.84     258 2477.64
   295.7 2477.15   299.2  2476.8   304.8 2474.55   309.8 2473.53     320  2473.2
   327.4 2473.47   332.6 2474.55   342.8  2475.5   369.6  2474.8   380.1 2479.34
   387.2 2481.08   408.8 2483.57   426.2 2487.75     446 2491.42   545.4 2493.62
#Mann= 10 ,-1 , 0
       0     .06       0       7     .12       0   37.53     .06       0
   68.06     .12       0  159.66    .016       0  251.26     .06       0
  287.31     .12       0   304.8     .04       0   332.6     .12       0
  441.01     .06       0
Bank Sta=304.8,332.6
XS Rating Curve= 0 ,0
Exp/Cntr=0.5,0.3

Type RM Length L Ch R = 1 ,14141   ,322.6,390.1,203.6
XS GIS Cut Line= 4
      2045163.56       342269.77      2045422.64      342357.797
     2045509.666      342445.824     2045745.739      342486.837
#Sta/Elev= 30
       0 2524.17    16.6  2519.5    38.2 2512.16    51.2 2505.07    65.1 2502.43
    92.8 2500.78     112 2496.39   122.2 2495.18   148.2 2494.92   164.9 2495.89
   206.3  2494.7   240.4 2491.33   252.2 2488.82     273 2489.75   296.1 2482.71
   306.6 2475.28   324.6 2475.01   328.7 2473.69   333.8 2472.29   343.1 2472.19
   350.1 2473.67   354.7 2475.72   359.4 2476.68   401.7 2476.78   421.7 2477.78
     445 2482.61   461.5 2488.07     470 2488.91   489.9 2490.01     637 2492.49
#Mann= 8 ,-1 , 0
       0     .12       0   85.83     .06       0   96.59     .12       0
  188.41    .016       0  276.61     .12       0   328.7     .04       0
   350.1     .12       0  488.35     .06       0
Bank Sta=328.7,350.1
XS Rating Curve= 0 ,0
Exp/Cntr=0.3,0.1

Type RM Length L Ch R = 1 ,13751   ,212.4,286.7,287.4
XS GIS Cut Line= 4
     2045153.557      342681.897      2045422.64      342697.902
     2045600.694      342603.873     2045803.757      342587.868
#Sta/Elev= 30
       0 2523.23      29 2521.37    48.7 2517.83    61.9 2516.99    68.4 2515.95
   124.3 2503.58   130.9 2500.51   137.5 2495.44   140.8 2494.61   155.4 2494.55
   170.3 2493.37   186.8 2490.68   239.4 2485.15   283.7  2476.8   362.6 2473.43
   402.4 2474.73   406.1 2474.24   409.8 2472.47   413.6 2470.94   420.7  2470.6
   428.4 2470.77   432.1  2472.4   439.5 2482.02   446.9 2486.44   452.4 2487.74
   469.2 2489.83   487.6 2489.25   614.2 2491.62     657 2493.97   674.6 2497.46
#Mann= 10 ,-1 , 0
       0    .016       0   49.33     .12       0   61.83    .016       0
   91.42     .12       0  121.01    .016       0  180.19     .06       0
  239.37     .12       0   409.8     .04       0   432.1     .12       0
   435.9     .06       0
Bank Sta=409.8,432.1
XS Rating Curve= 0 ,0
Exp/Cntr=0.3,0.1

Type RM Length L Ch R = 1 ,13465   ,272.2,276.9,280.2
XS GIS Cut Line= 4
     2045243.584      342736.914     2045531.673      342869.955
     2045579.688      342925.972     2045691.722      343007.997
#Sta/Elev= 30
       0 2511.08    12.2 2509.03    23.1 2506.42    30.3 2501.66    33.9 2500.26
    51.6 2500.58    90.7 2499.14    95.4 2497.48   106.2  2491.1   120.7 2487.33
   131.5 2486.13   153.3 2486.12   174.9 2485.26   218.2 2480.93   229.1 2480.59
   252.1 2477.88   283.3 2476.22   297.7 2474.56   315.8 2474.56   325.3 2473.53
   331.4 2471.56   335.4 2470.27   340.4 2470.47   346.22471.573     365    2477
   386.6 2482.32     405 2486.46   423.4 2489.49   451.9 2492.28     530 2496.25
#Mann= 11 ,-1 , 0
       0    .016       0    1.36     .06       0   16.67    .016       0
   66.43     .12       0   87.12     .06       0   131.5     .12       0
  157.57     .06       0  261.63     .12       0   331.4     .04       0
   346.2     .12       0  375.79     .06       0
Bank Sta=331.4,346.2
XS Rating Curve= 0 ,0
Exp/Cntr=0.3,0.1

Type RM Length L Ch R = 1 ,13188   ,322.4,309.4,241.4
XS GIS Cut Line= 4
     2045184.566      342870.955     2045296.601      343005.997
     2045363.621      343102.026     2045565.684      343166.046
#Sta/Elev= 30
       0 2515.38    28.2 2510.95    37.9 2509.02    42.2 2507.78    49.2 2504.65
    53.3 2504.28    72.5 2504.29    79.5 2503.54    84.2 2502.53   104.7  2495.9
   109.7 2494.82   130.4 2493.69   137.7 2490.94   148.1 2489.55   176.8  2488.2
   185.8  2485.2   197.8 2483.78   213.8 2475.23   217.8 2473.84   227.52471.603
   234.1 2470.17   246.3 2471.52   250.4 2472.22   257.8 2475.03   261.8 2476.08
   285.8  2479.7   319.4 2483.58   350.5 2486.51   389.5 2489.23   504.5 2493.96
#Mann= 7 ,-1 , 0
       0     .12       0    1.84     .06       0    48.1    .016       0
   94.36     .06       0  216.05     .12       0   227.5     .04       0
   246.3     .12       0
Bank Sta=227.5,246.3
XS Rating Curve= 0 ,0
Exp/Cntr=0.3,0.1

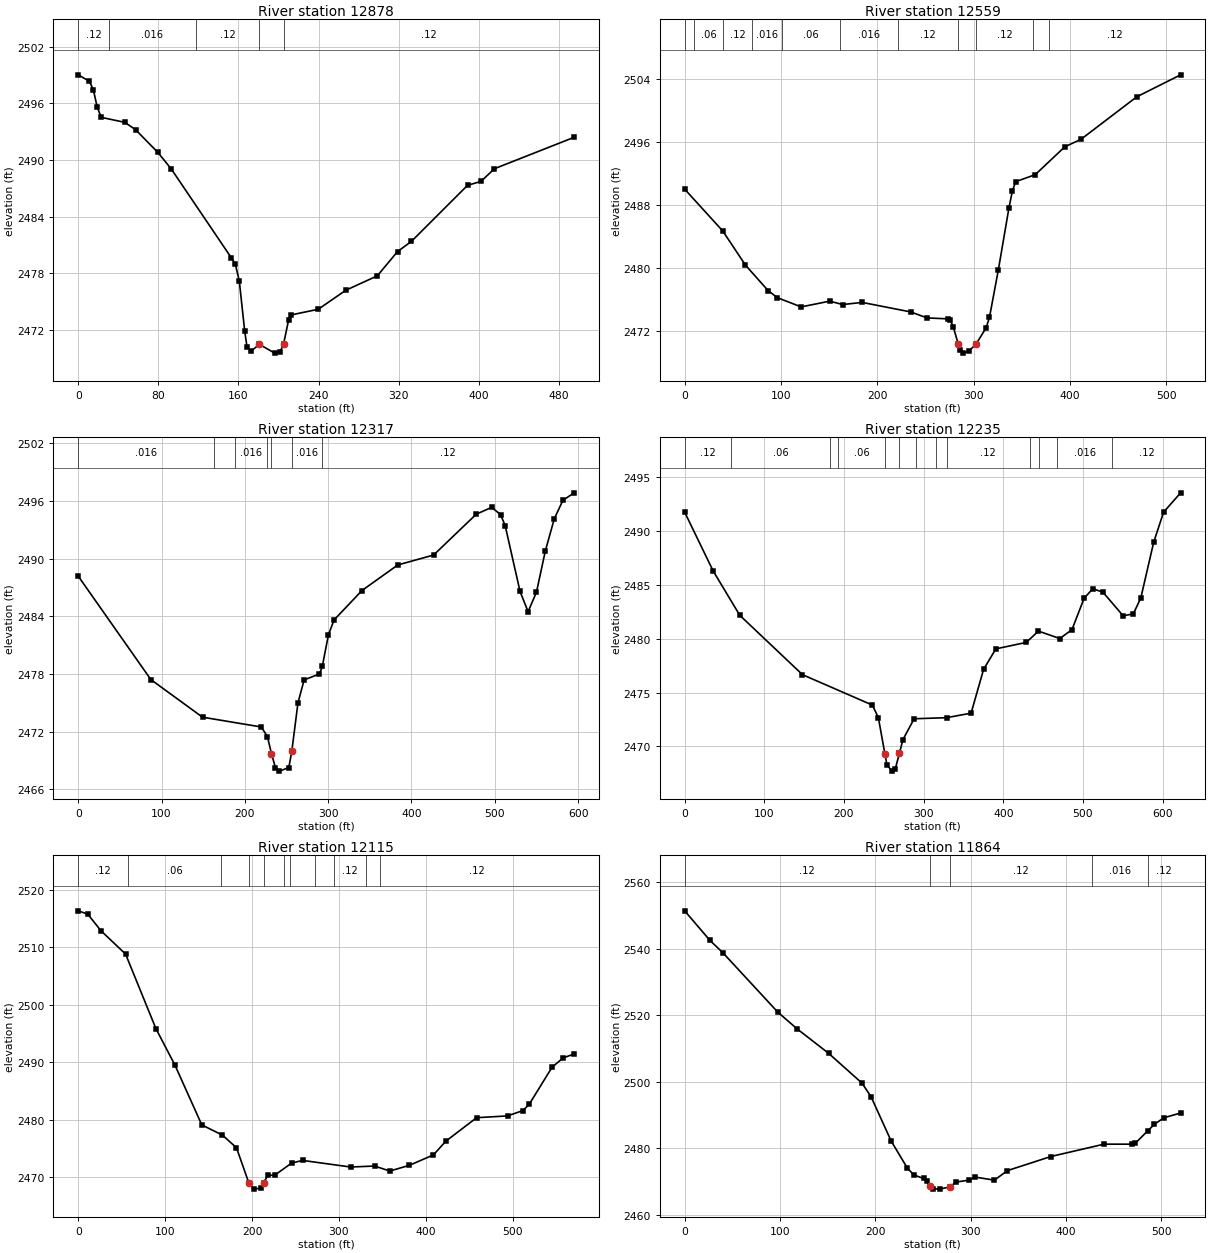
Type RM Length L Ch R = 1 ,12878   ,292.5,319,321.8
XS GIS Cut Line= 3
     2045071.532      343370.109     2045321.608      343204.058
     2045513.668      343171.048
#Sta/Elev= 30
       0 2499.02    11.1 2498.34    15.1 2497.44      19 2495.59      23 2494.52
    46.6 2493.99    57.4  2493.2    79.5 2490.81    92.9 2489.06   152.9 2479.65
   156.8    2479   160.8 2477.21   166.2  2471.9   168.6 2470.18   172.6 2469.78
   180.8  2470.5   196.2 2469.57   201.7 2469.74  204.99 2470.53     210 2473.06
     212  2473.6   239.6 2474.21   267.1 2476.22   298.6 2477.75   318.8 2480.32
   332.6 2481.39   388.7 2487.33   402.1 2487.74   415.4 2489.08   495.1 2492.41
#Mann= 5 ,-1 , 0
       0     .12       0   30.72    .016       0  117.51     .12       0
   180.8     .04       0  204.99     .12       0
Bank Sta=180.8,204.99
XS Rating Curve= 0 ,0
Exp/Cntr=0.3,0.1

Type RM Length L Ch R = 1 ,12559   ,222.9,241.9,254.3
XS GIS Cut Line= 3
2045104.53854862343417.199269899      2045327.61      343467.139
     2045603.695      343542.162
#Sta/Elev= 30
       0 2490.04    39.6 2484.72    63.1 2480.39    86.6 2477.16    96.2 2476.26
   120.9 2475.09   150.5 2475.82     164 2475.39   184.2 2475.66   234.6 2474.45
   251.6 2473.69   273.5 2473.57   275.4 2473.48   278.8 2472.54   283.92470.383
   285.6 2469.68     289 2469.22   294.9 2469.46   302.6  2470.4   312.8 2472.43
   316.3 2473.75   325.5 2479.77   336.6 2487.71     340 2489.75   343.4 2490.99
   363.8 2491.88   394.4 2495.41   411.4 2496.38   469.2 2501.77   514.7 2504.56
#Mann= 11 ,-1 , 0
       0     .12       0    9.76     .06       0   40.01     .12       0
   70.25    .016       0   100.5     .06       0     161    .016       0
  221.49     .12       0   283.9     .04       0   302.6     .12       0
   361.6     .04       0   377.8     .12       0
Bank Sta=283.9,302.6
XS Rating Curve= 0 ,0
Exp/Cntr=0.5,0.3

Type RM Length L Ch R = 1 ,12317   ,80.9,82.4,92.4
XS GIS Cut Line= 4
     2045108.543      343434.128     2045207.573      343619.185
     2045256.588      343716.215     2045475.656      343885.267
#Sta/Elev= 30
       0 2488.19    87.2 2477.43   149.2 2473.52   219.8  2472.5   227.1  2471.5
     232 2469.72   236.8 2468.25   241.6 2467.91   252.8 2468.28   256.4 2469.99
   263.8 2475.02   271.2  2477.4   289.6 2478.01     293  2478.8   300.3 2482.07
   307.1 2483.63   340.6 2486.69   383.6 2489.35   426.6 2490.38   477.8 2494.63
   496.4 2495.34     507 2494.58   512.5 2493.44   530.3 2486.61     540 2484.49
   550.1 2486.53   560.7 2490.81   571.5 2494.16   581.8 2496.07   595.3 2496.85
#Mann= 7 ,-1 , 0
       0    .016       0  163.59     .12       0  188.67    .016       0
  226.95     .12       0     232     .04       0   256.4    .016       0
  292.45     .12       0
Bank Sta=232,256.4
XS Rating Curve= 0 ,0
Exp/Cntr=0.5,0.3

Type RM Length L Ch R = 1 ,12235   ,124.8,119.6,96.2
XS GIS Cut Line= 4
2045041.21360617343455.209544207      2045130.55      343624.187
     2045167.561      343743.224     2045430.642      343901.272
#Sta/Elev= 30
       0 2491.77    35.7 2486.31    69.2 2482.18   147.9 2476.66   235.7 2473.83
   243.2 2472.66   251.4 2469.29     254 2468.27   260.4 2467.69   264.5 2467.91
   269.7 2469.37   274.1 2470.63   288.1 2472.56   328.8 2472.66   359.6 2473.08
   375.3 2477.15   390.7 2479.06   428.9 2479.66   444.2 2480.71     471 2480.02
   486.3 2480.85   501.6 2483.78   512.5 2484.65   525.2 2484.33   550.7 2482.12
   563.4 2482.33   572.7 2483.79   588.9 2488.98   601.3 2491.77   622.7 2493.57
#Mann= 13 ,-1 , 0
       0     .12       0   58.68     .06       0  182.76     .12       0
  192.85     .06       0   251.4     .04       0   269.7     .06       0
  290.35     .12       0   315.6     .04       0   328.8     .12       0
  433.62    .016       0  444.92     .12       0  468.08    .016       0
  536.99     .12       0
Bank Sta=251.4,269.7
XS Rating Curve= 0 ,0
Exp/Cntr=0.5,0.3

Type RM Length L Ch R = 1 ,12115   ,255.8,251.1,117.1
XS GIS Cut Line= 4
2044894.54995567343626.723614988     2045022.516      343714.215
     2045074.532      343788.237     2045374.625      343913.276
#Sta/Elev= 30
       0 2516.34      11 2515.76    26.3 2512.85    54.5 2508.81    89.4 2495.83
   111.3 2489.47   142.2 2479.06   165.9 2477.29   182.1 2475.08   196.2 2469.01
     202 2467.88     210 2468.05   213.42468.932     218 2470.29     226  2470.3
   245.6 2472.42   258.2 2472.88   313.4 2471.73     341  2471.9   358.5 2471.03
   381.1 2472.03   408.7 2473.84   422.9 2476.22   458.4 2480.32     494 2480.63
   511.6 2481.56   518.9 2482.65   545.3 2489.13     558 2490.73   570.6 2491.42
#Mann= 11 ,-1 , 0
       0     .12       0   57.79     .06       0  164.84     .12       0
   196.2     .04       0   213.4     .12       0  236.21     .06       0
  244.03     .12       0  271.89     .06       0  294.21     .12       0
   330.8     .04       0   347.2     .12       0
Bank Sta=196.2,213.4
XS Rating Curve= 0 ,0
Exp/Cntr=0.3,0.1

Type RM Length L Ch R = 1 ,11864   ,217.7,219.2,220.2
XS GIS Cut Line= 3
     2044858.466      343989.299      2045162.56      343908.274
     2045367.623      343919.278
#Sta/Elev= 30
       0 2551.43    26.4 2542.57      40 2538.85    97.7 2520.96   118.1  2515.9
   151.1 2508.56     186 2499.62   195.5 2495.52   216.5 2482.25   233.5  2474.1
   240.3 2472.04   250.5 2470.97   253.9 2470.09   257.1  2468.6   260.7 2467.85
   267.4 2467.77   278.6 2468.47   284.4 2469.89     298 2470.46   304.8 2471.38
   324.8 2470.47   338.5 2473.34     384 2477.57   439.8 2481.29   469.4 2481.28
   472.7 2481.59   485.8 2485.34   492.4  2487.2   502.3 2489.19   520.1 2490.66
#Mann= 5 ,-1 , 0
       0     .12       0   257.1     .04       0   278.6     .12       0
  426.64    .016       0   485.8     .12       0
Bank Sta=257.1,278.6
XS Rating Curve= 0 ,0
Exp/Cntr=0.3,0.1

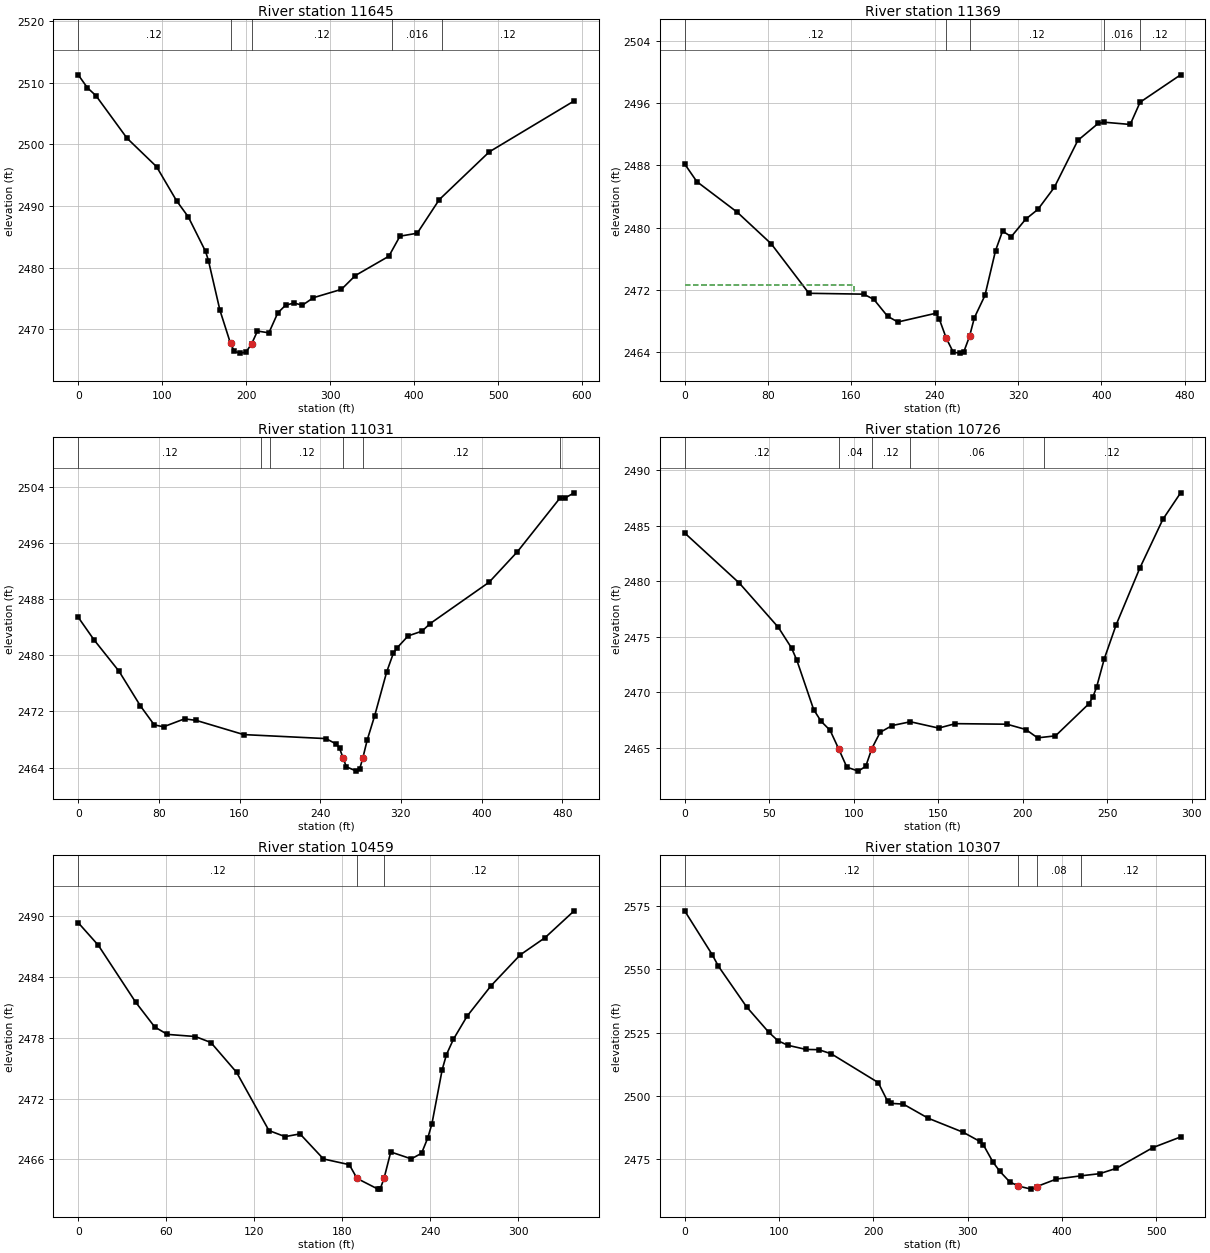
Type RM Length L Ch R = 1 ,11645   ,249.2,275.8,258.2
XS GIS Cut Line= 3
      2045001.51      344182.359     2045215.576      344116.338
     2045577.687      344058.321
#Sta/Elev= 30
       0 2511.25    10.9 2509.16    21.2 2507.86    58.1 2500.98    93.3 2496.36
   117.3  2490.8   131.1 2488.22   151.7 2482.61   155.1 2481.14   168.8 2473.08
   181.4  2467.7     186  2466.4   192.9 2466.13   199.8 2466.29   206.6 2467.65
   213.5 2469.71   227.1 2469.42   237.7 2472.65     247  2473.9     257 2474.25
     267  2473.9   280.2 2475.12   313.5 2476.47   330.1 2478.71     370 2481.84
   383.2 2485.09   403.8 2485.57     430 2491.01   489.6 2498.76   590.7 2507.02
#Mann= 5 ,-1 , 0
       0     .12       0   181.4     .04       0   206.6     .12       0
  373.26    .016       0  433.09     .12       0
Bank Sta=181.4,206.6
XS Rating Curve= 0 ,0
Exp/Cntr=0.3,0.1

Type RM Length L Ch R = 1 ,11369   ,178.7,338.3,305.9
XS GIS Cut Line= 4
      2045066.53       344349.41     2045301.602      344341.408
     2045377.626      344322.402     2045513.668      344233.374
#Sta/Elev= 30
       0 2488.19    11.7 2485.92    50.4    2482    83.1 2477.93   119.3 2471.57
   171.9 2471.46   181.7 2470.78   194.8 2468.62   204.7 2467.88     241    2469
   244.3 2468.33   251.1 2465.82   257.9 2463.99   264.6 2463.88   268.1 2464.08
   273.5 2466.03   278.2 2468.44   288.3 2471.29   298.5 2477.06   305.2 2479.56
   313.6 2478.85   327.4 2481.09   339.2 2482.36   354.9 2485.18   377.5 2491.22
     397  2493.4   402.8 2493.56   427.8 2493.27   437.3 2496.13   476.2 2499.65
#Mann= 5 ,-1 , 0
       0     .12       0   251.1     .04       0   273.5     .12       0
   402.8    .016       0   437.3     .12       0
#XS Ineff= 2 , 0
          163.04  2472.6
Permanent Ineff=
       F       F
Bank Sta=251.1,273.5
XS Rating Curve= 0 ,0
Exp/Cntr=0.3,0.1

Type RM Length L Ch R = 1 ,11031   ,288,305.4,263.1
XS GIS Cut Line= 4
     2045079.534      344359.413     2045250.587      344527.465
     2045263.591      344601.488     2045371.624      344741.531
#Sta/Elev= 30
       0  2485.4    15.6  2482.2    40.5 2477.71    61.6  2472.8    75.4 2470.08
    84.6 2469.81   105.4 2470.94     117 2470.72   164.1  2468.7   245.7 2468.13
   255.9 2467.35   259.2 2466.74   262.7 2465.35   265.9 2464.12   275.9  2463.5
   279.2 2463.85   282.32465.406   286.6 2467.94   293.9 2471.34   305.9 2477.62
   312.5 2480.27   316.1 2481.03   327.2 2482.75   340.9 2483.42     349  2484.5
   407.5 2490.39   435.6 2494.74   477.6 2502.34   482.3 2502.34   491.8 2503.11
#Mann= 6 ,-1 , 0
       0     .12       0  181.46     .06       0  190.26     .12       0
   262.7     .04       0   282.3     .12       0  477.59    .016       0
Bank Sta=262.7,282.3
XS Rating Curve= 0 ,0
Exp/Cntr=0.3,0.1

Type RM Length L Ch R = 1 ,10726   ,200.5,266.6,220
XS GIS Cut Line= 2
     2044938.491       344607.49     2045157.558       344802.55
#Sta/Elev= 30
       0 2484.35    32.4 2479.82    55.4 2475.84    63.2 2473.98    66.3 2472.89
    76.3 2468.42    80.7 2467.37      86 2466.56      91 2464.91    95.9 2463.24
   102.7 2462.88   107.1 2463.32   110.7 2464.92   115.6 2466.38   122.7 2466.99
   133.5 2467.33   150.2 2466.76   160.1 2467.16   190.6 2467.11   201.8 2466.63
   208.7 2465.88   219.3 2466.06   238.9 2468.93   241.3 2469.52   243.6 2470.45
   248.2 2473.03   255.2 2476.08   269.1 2481.16   282.8 2485.58   293.3 2487.97
#Mann= 5 ,-1 , 0
       0     .12       0      91     .04       0   110.7     .12       0
  133.27     .06       0  212.37     .12       0
Bank Sta=91,110.7
XS Rating Curve= 0 ,0
Exp/Cntr=0.3,0.1

Type RM Length L Ch R = 1 ,10459   ,165.9,151.8,127.8
XS GIS Cut Line= 4
      2044816.12      344706.742     2044921.708      344832.337
      2044953.94      344914.5842045020.88631864344968.363654911
#Sta/Elev= 30
       0 2489.32    13.7  2487.1    39.1 2481.51    52.2 2479.05    60.8 2478.32
    79.9 2478.11    90.5 2477.52     108 2474.59   130.1 2468.85   141.1 2468.25
   151.3 2468.52   167.3 2466.05   184.9 2465.49   190.22464.134   204.5 2463.08
     206  2463.1   208.62464.133   213.2 2466.74   227.2 2466.06   234.2 2466.61
   238.5 2468.14   241.3 2469.53   248.3 2474.86   251.2 2476.33   255.9 2477.83
   265.3 2480.12   281.6 2483.11   301.5 2486.15   318.4 2487.84   338.3 2490.49
#Mann= 3 ,-1 , 0
       0     .12       0   190.2     .04       0   208.6     .12       0
Bank Sta=190.2,208.6
XS Rating Curve= 0 ,0
Exp/Cntr=0.3,0.1

Type RM Length L Ch R = 1 ,10307   ,263.3,255,229.3
XS GIS Cut Line= 3
     2044454.897      344871.237     2044737.206      344915.696
     2044960.608        345003.5
#Sta/Elev= 30
       0 2573.18    29.2 2555.85    35.8 2551.27    65.7  2535.2    88.9 2525.29
    98.9 2521.83   109.3 2520.05   128.8 2518.39   142.1 2518.31   155.4 2516.67
   205.2  2505.3   215.1 2497.94   218.5 2497.09   231.8 2496.79   258.3 2491.19
   295.4 2485.64     313 2482.04   316.6 2480.73   326.9 2473.85   334.2 2470.19
   344.6 2466.06   353.9 2464.39   367.3 2463.19   373.4 2464.22   394.1 2467.17
   420.5 2468.47   439.9 2469.29   457.6  2471.4   496.4  2479.6   525.8 2483.81
#Mann= 4 ,-1 , 0
       0     .12       0   353.9     .04       0   373.4     .08       0
   420.5     .12       0
Bank Sta=353.9,373.4
XS Rating Curve= 0 ,0
Exp/Cntr=0.5,0.3