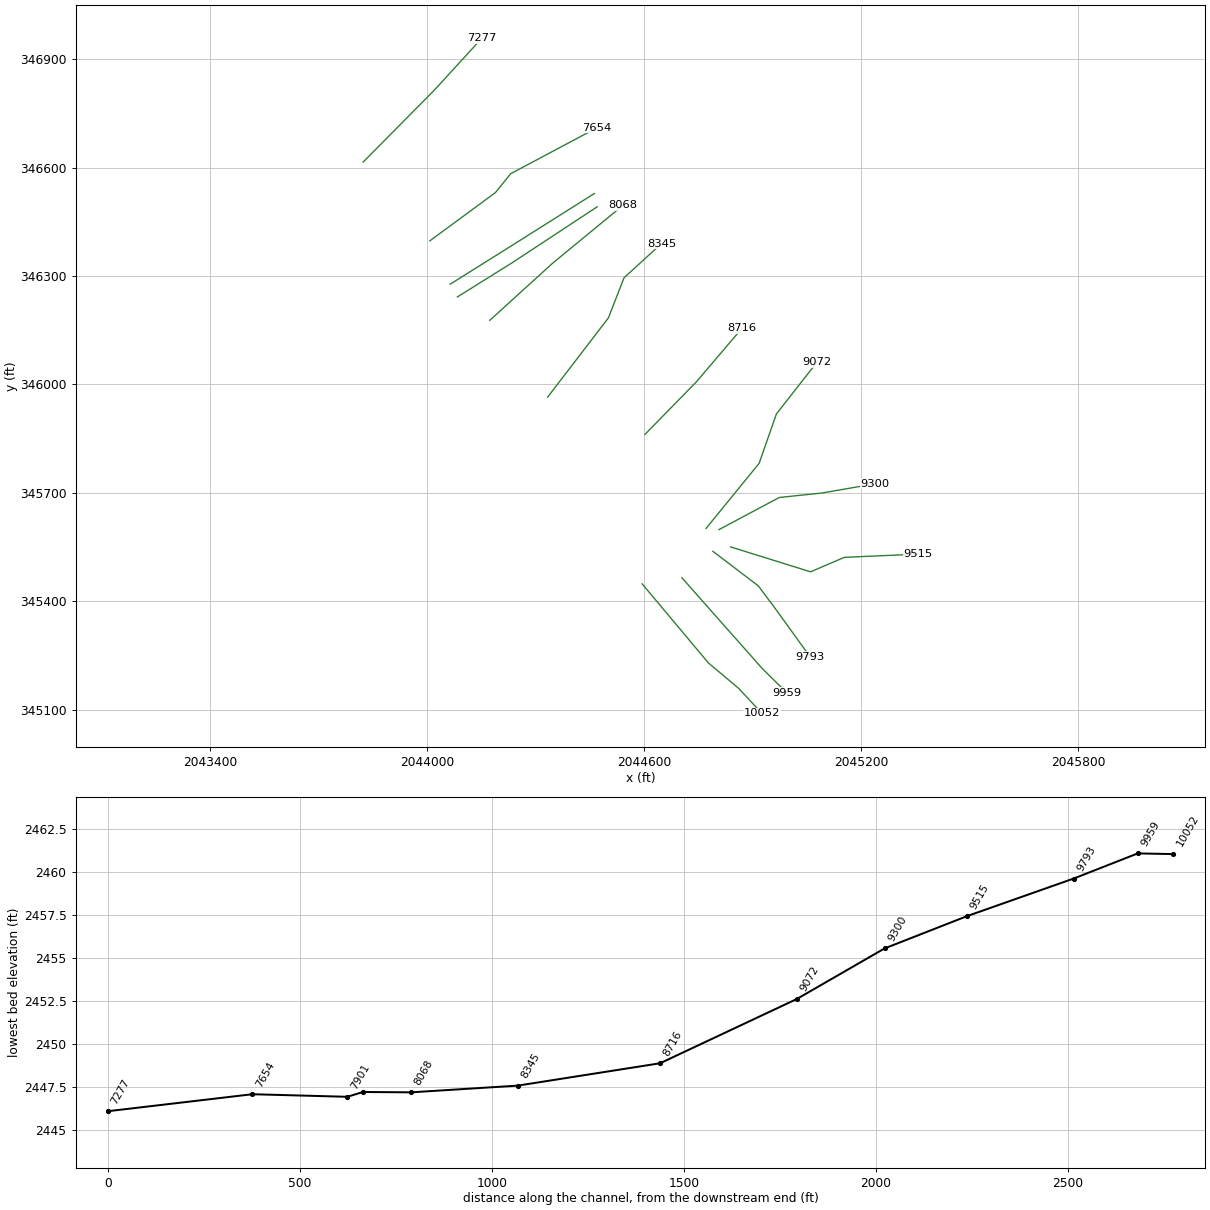
HEC-RAS study LTSEWELLCK.prj: LTSEWELLCK

--- LTSEWELLCK.g01 (geometry) --- (continued)

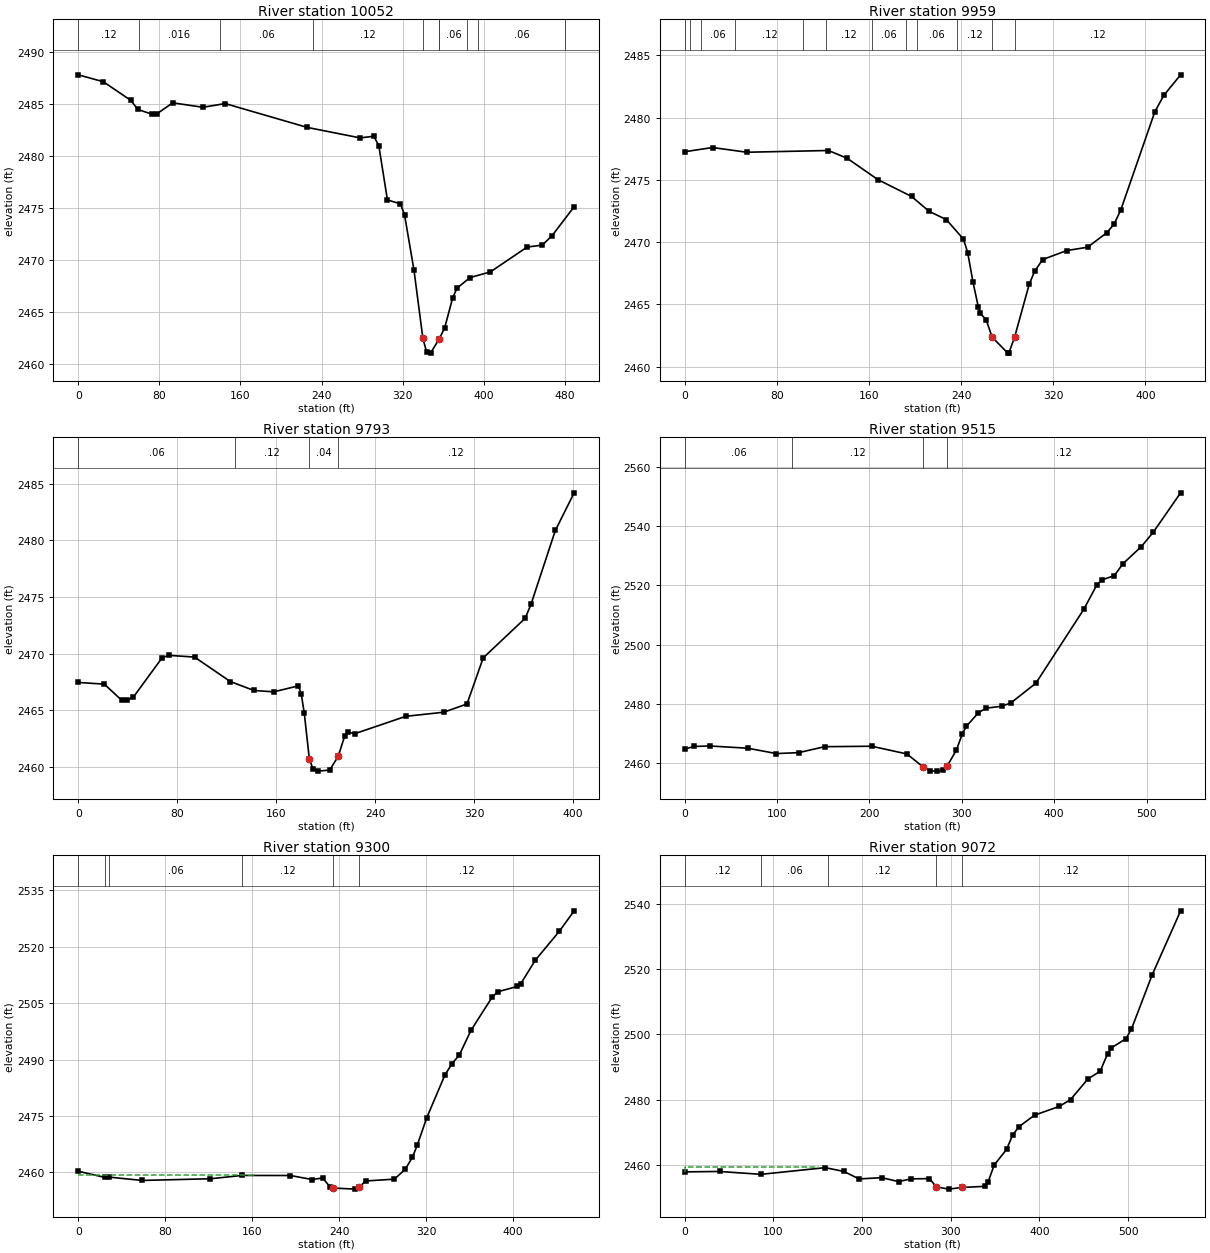
Type RM Length L Ch R = 1 ,10052   ,95.8,92.9,91.5
XS GIS Cut Line= 4
     2044593.829      345448.082     2044777.219      345229.125
     2044860.578      345159.1042044925.07078325345089.754084006
#Sta/Elev= 30
       0 2487.78    24.7 2487.12    51.7 2485.34    58.9 2484.45    72.7    2484
    77.3 2484.01    93.2 2485.09   123.1 2484.66   144.9 2485.02   225.8 2482.73
   278.1 2481.72   291.6 2481.88   296.5 2480.98     305 2475.76   317.9 2475.38
   321.9 2474.32   331.2 2469.02     3402462.449   343.6 2461.17   347.5 2461.04
     3562462.389   361.5 2463.47   369.3 2466.33   373.6 2467.28   386.5  2468.3
   406.5 2468.84   442.8 2471.23   457.7 2471.42   467.4 2472.32   489.2 2475.11
#Mann= 10 ,-1 , 0
       0     .12       0    59.8    .016       0  139.76     .06       0
  231.77     .12       0     340     .04       0     356     .12       0
  356.19     .06       0  383.84     .12       0  394.79     .06       0
  480.57     .12       0
Bank Sta=340,356
XS Rating Curve= 0 ,0
Exp/Cntr=0.5,0.3

Type RM Length L Ch R = 1 ,9959    ,163.9,166.5,158.7
XS GIS Cut Line= 3
     2044703.863      345464.753     2044926.153      345213.565
2044993.93084521 345146.54922116
#Sta/Elev= 30
       0 2477.26    24.2  2477.6    53.9 2477.22   124.9 2477.36   141.2 2476.73
   167.8 2475.02     197 2473.67   212.3 2472.47   227.2 2471.81   242.1 2470.24
   245.8 2469.15   250.4 2466.78   255.1 2464.75   256.9 2464.27   261.9 2463.74
     2672462.365   280.6 2461.08   281.7 2461.13   286.6 2462.39   299.2 2466.61
   303.9 2467.65   310.9  2468.6   331.8 2469.32   349.9 2469.59   366.6 2470.75
     373 2471.46   378.8  2472.6   408.3 2480.47   416.1 2481.79   430.7 2483.44
#Mann= 12 ,-1 , 0
       0     .06       0    4.59    .016       0   13.95     .06       0
   44.04     .12       0  103.09     .06       0  122.92     .12       0
  162.36     .06       0  192.23     .12       0   201.8     .06       0
   236.8     .12       0     267     .04       0   286.6     .12       0
Bank Sta=267,286.6
XS Rating Curve= 0 ,0
Exp/Cntr=0.5,0.3

Type RM Length L Ch R = 1 ,9793    ,250.1,278.1,272.9
XS GIS Cut Line= 4
     2044789.445      345538.109     2044915.039      345442.524
     2044963.943      345376.9492045058.21424786 345246.22002645
#Sta/Elev= 30
       0 2467.45    21.1  2467.3    35.2 2465.87    39.1 2465.86    44.6 2466.16
    67.9 2469.64    73.4 2469.84      94 2469.69   122.9 2467.53     142 2466.74
   158.1 2466.62     178 2467.15   180.3  2466.4   182.7 2464.73   186.8 2460.69
   189.7 2459.82   193.6 2459.62   203.2 2459.71   210.1 2460.92   215.4 2462.73
   217.9 2463.05   223.6 2462.93   264.8 2464.46   295.4 2464.82   314.2 2465.55
   327.3 2469.62   361.2 2473.11   365.9 2474.34   385.6 2480.87   400.8 2484.19
#Mann= 4 ,-1 , 0
       0     .06       0  126.78     .12       0   186.8     .04       0
   210.1     .12       0
Bank Sta=186.8,210.1
XS Rating Curve= 0 ,0
Exp/Cntr=0.3,0.1

Type RM Length L Ch R = 1 ,9515    ,215.7,214.7,201.3
XS GIS Cut Line= 4
     2044838.349      345550.335     2045059.528      345481.425
      2045152.89      345521.437     2045356.286      345530.329
#Sta/Elev= 30
       0 2464.87      10 2465.74    27.2  2465.9    68.4 2465.14    99.3 2463.34
   123.4 2463.66   151.5 2465.66   202.4 2465.81   240.5 2463.22   257.92458.891
   265.5 2457.56   272.7 2457.43   279.8  2457.7   284.12459.138   294.1  2464.5
   300.5 2469.99   304.8 2472.46     318 2477.14   326.2 2478.63   343.2 2479.29
     353 2480.39   380.1 2487.03   431.9 2511.87   446.2 2520.19   451.6  2521.8
   465.1  2523.3   474.5 2527.32   494.3 2533.05   507.4 2537.97   536.8 2551.15
#Mann= 4 ,-1 , 0
       0     .06       0  116.32     .12       0   257.9     .04       0
   284.1     .12       0
Bank Sta=257.9,284.1
XS Rating Curve= 0 ,0
Exp/Cntr=0.3,0.1

Type RM Length L Ch R = 1 ,9300    ,160.3,228.3,241.6
XS GIS Cut Line= 4
     2044806.116      345598.128     2044972.834      345687.044
     2045089.537       345699.27      2045237.36      345724.833
#Sta/Elev= 30
       0  2460.3    24.4 2458.68    28.7 2458.74    58.7 2457.86   121.7 2458.31
   150.9 2459.19   195.3 2459.17     215 2458.11   224.9 2458.51   231.5 2456.22
   234.6 2455.84   254.6 2455.55   258.5 2456.06   264.5 2457.72   290.9  2458.2
   300.8  2460.8   307.4 2463.96     312 2467.27   320.7 2474.55   337.5 2485.97
     344 2488.93   350.7 2491.24   361.3 2497.73   380.7 2506.53   385.8 2508.01
     404 2509.44   407.3 2510.22   420.6 2516.43   442.6 2524.09   456.3 2529.55
#Mann= 6 ,-1 , 0
       0     .06       0    24.4     .12       0    28.7     .06       0
   150.9     .12       0   234.6     .04       0   258.5     .12       0
#XS Ineff= 2 , 0
             163  2459.3
Permanent Ineff=
       F       F
Bank Sta=234.6,258.5
XS Rating Curve= 0 ,0
Exp/Cntr=0.3,0.1

Type RM Length L Ch R = 1 ,9072    ,318.9,356.1,275.7
XS GIS Cut Line= 4
      2044770.55      345601.462     2044917.262      345781.517
     2044965.054      345918.226     2045077.311      346061.604
#Sta/Elev= 30
       0 2457.89    39.3 2458.02      86 2457.14   158.6 2459.19   179.5 2458.02
   196.7 2455.73   222.1 2456.12   241.3 2454.92   255.2 2455.76     276 2455.82
   283.82453.308   297.8 2452.61   312.72453.126   338.6 2453.46   342.1  2454.8
     349    2460   362.9 2464.76   369.8 2469.16   376.8 2471.71   394.5 2475.27
   422.6 2477.97   435.1 2480.04   454.7 2486.37   468.5 2488.71   476.8 2494.05
     481 2495.86   497.6  2498.7   503.8 2501.68   527.1 2518.24   559.2 2537.86
#Mann= 5 ,-1 , 0
       0     .12       0   85.93     .06       0  162.13     .12       0
   283.8     .04       0   312.7     .12       0
#XS Ineff= 2 , 0
          150.65 2459.29
Permanent Ineff=
       F       F
Bank Sta=283.8,312.7
XS Rating Curve= 0 ,0
Exp/Cntr=0.3,0.1

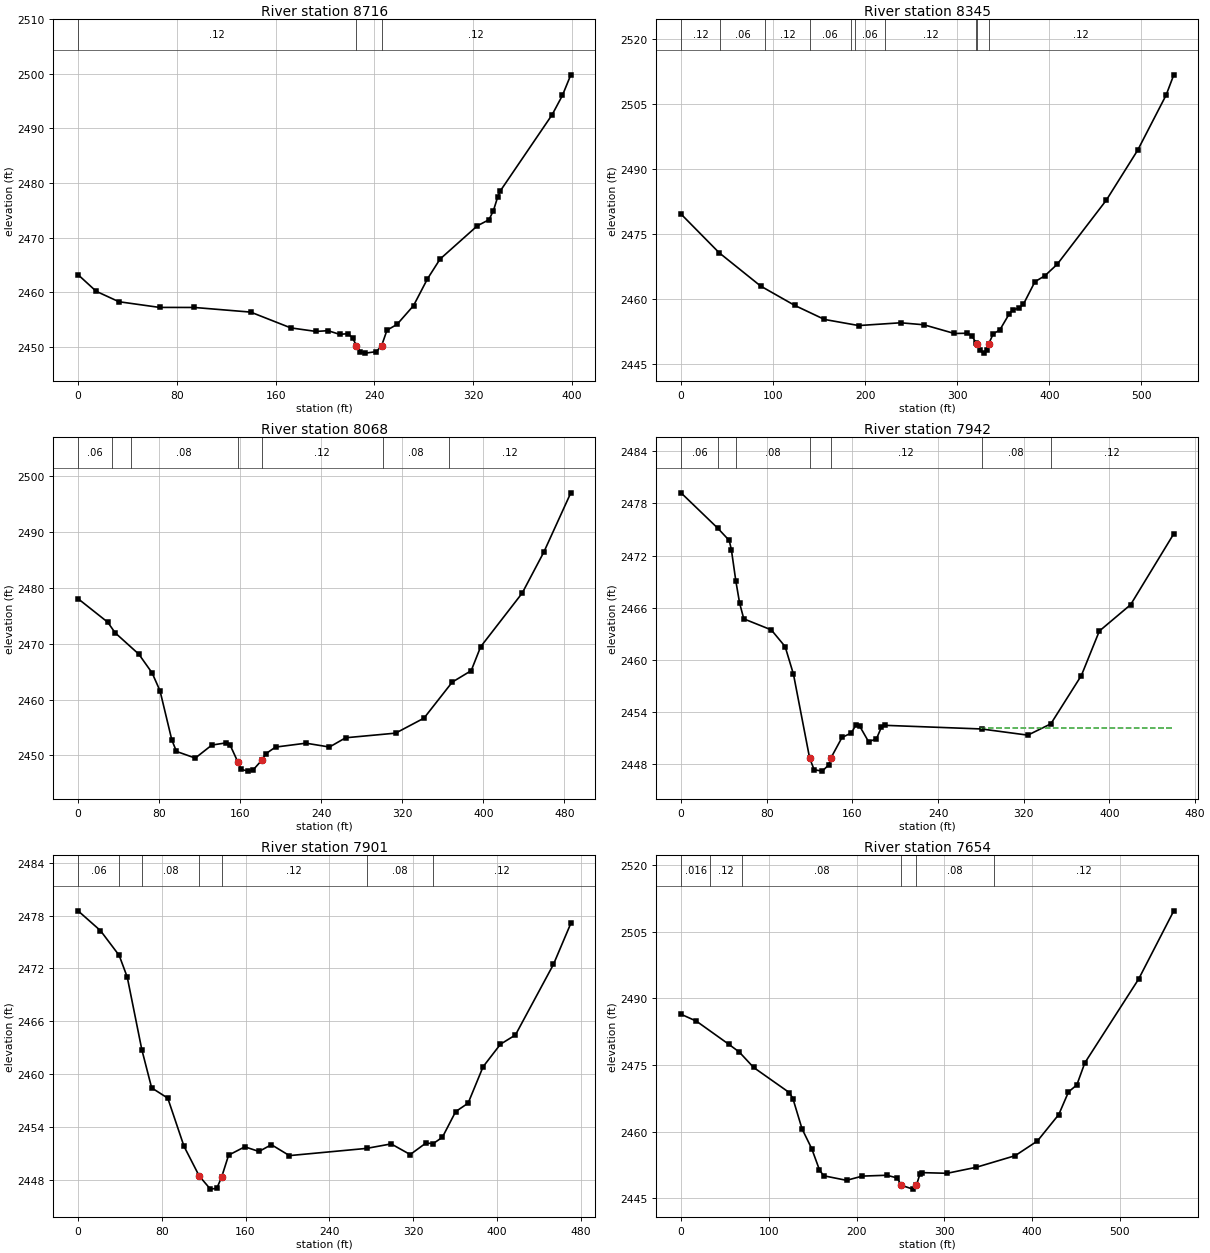
Type RM Length L Ch R = 1 ,8716    ,324.8,370.5,327.6
XS GIS Cut Line= 3
     2044601.609      345861.542     2044743.875      346007.142
     2044870.581      346156.077
#Sta/Elev= 30
       0 2463.23    14.7 2460.19    33.1 2458.28      66 2457.24    94.2 2457.23
   139.8 2456.38   172.3 2453.49   192.8 2452.84   202.5 2452.98   211.8 2452.31
   218.8 2452.43   222.3 2451.65   225.52450.251   228.7 2449.06   232.7 2448.87
   241.6 2449.14   245.9 2450.25   250.2 2453.07   258.3 2454.12   271.7 2457.56
     283 2462.47   293.2 2466.09   323.4 2472.18   332.8 2473.29   336.4 2474.95
   339.8  2477.4   342.1  2478.6     384 2492.53   392.3 2496.05   399.1 2499.82
#Mann= 3 ,-1 , 0
       0     .12       0   225.5     .04       0   245.9     .12       0
Bank Sta=225.5,245.9
XS Rating Curve= 0 ,0
Exp/Cntr=0.3,0.1

Type RM Length L Ch R = 1 ,8345    ,253.1,277.3,202.6
XS GIS Cut Line= 4
     2044332.637      345964.907     2044500.467      346183.864
     2044543.814      346295.009     2044647.179      346389.482
#Sta/Elev= 30
       0 2479.65    41.5 2470.71    86.5 2463.04   123.4 2458.59   155.8 2455.34
     193 2453.93   238.5 2454.57   263.8 2454.11   296.9  2452.1     311 2452.16
     316 2451.53   320.52449.907   321.1 2449.64     325 2448.19   328.7 2447.57
   332.1 2448.36     334 2449.63   339.1 2452.03   346.2  2452.9   356.7  2456.7
   360.3 2457.54   367.3 2457.97   371.8 2458.82   384.4 2464.05   395.2 2465.42
   408.6 2468.07     462 2482.88     496 2494.39   526.9 2507.11   535.2 2511.77
#Mann= 10 ,-1 , 0
       0     .12       0   42.76     .06       0   91.31     .12       0
  139.87     .06       0  184.23     .12       0  188.42     .06       0
  221.45     .12       0   320.5     .04       0   321.1     .04       0
     334     .12       0
Bank Sta=321.1,334
XS Rating Curve= 0 ,0
Exp/Cntr=0.3,0.1

Type RM Length L Ch R = 1 ,8068    ,95.6,125.5,70.4
XS GIS Cut Line= 3
     2044172.588      346177.195     2044345.975      346335.021
     2044540.479       346495.07
#Sta/Elev= 30
       0 2478.09    29.2 2473.89    36.7 2471.96      60 2468.14    73.1 2464.78
    80.9 2461.57    92.5 2452.79    97.1 2450.71   115.7 2449.52     132 2451.85
   145.9 2452.24   150.1 2451.84   157.5  2448.9   160.8  2447.5   167.8 2447.18
   172.3  2447.3   181.1 2449.09   185.4 2450.31   194.9 2451.49   224.9 2452.19
   248.1  2451.5   264.1 2453.16   313.4 2453.99   341.4 2456.68   369.3 2463.14
     388 2465.19   397.3 2469.47   438.3 2479.09   459.6 2486.42   486.3 2497.07
#Mann= 7 ,-1 , 0
       0     .06       0   33.48     .12       0   51.89     .08       0
   157.5     .04       0   181.1     .12       0  300.47     .08       0
  365.62     .12       0
Bank Sta=157.5,181.1
XS Rating Curve= 0 ,0
Exp/Cntr=0.5,0.3

Type RM Length L Ch R = 1 ,7942    ,40.9,40.8,40.8
XS GIS Cut Line= 3
2044082.97546705346241.9342818372044233.26861519346335.785461679
2044469.53731969346491.329025473
#Sta/Elev= 30
       0 2479.22    34.3 2475.15      45 2473.74      47 2472.69    51.2 2469.06
    54.7 2466.53    58.6 2464.72    84.3 2463.45    97.2 2461.53     105 2458.34
   120.12448.686   124.3 2447.36   131.9  2447.2   137.9 2447.92   139.8 2448.68
   150.3 2451.07   159.1  2451.6     163 2452.46   166.9 2452.36   175.1 2450.59
   182.4  2450.9   187.1 2452.25   190.3 2452.47   280.6 2452.05   323.8 2451.34
   345.3 2452.64   373.8  2458.2   390.6 2463.32   419.8 2466.35   460.1 2474.51
#Mann= 7 ,-1 , 0
       0     .06       0    34.3     .12       0    51.2     .08       0
   120.1     .04       0   139.8     .12       0   280.6     .08       0
   345.3     .12       0
#XS Ineff= 2 , 0
                          280.38         2452.21
Permanent Ineff=
       F       F
Bank Sta=120.1,139.8
XS Rating Curve= 0 ,0
Exp/Cntr(USF)=0,0
Exp/Cntr=0.5,0.3

Type RM Length L Ch R = 1 ,7901    ,183.7,247.1,190.3
XS GIS Cut Line= 3
2044063.28640834346277.3745875122044228.67450149346381.070296708
 2044461.6616962346528.081935062
#Sta/Elev= 30
       0 2478.55    21.4  2476.3    39.3 2473.48      47 2471.01    60.9 2462.78
    70.3 2458.43    85.7 2457.26   101.2 2451.79   115.7 2448.42   126.4 2446.92
   132.5 2447.01   137.1 2448.27   143.8 2450.78   159.3 2451.73   172.8  2451.2
   184.7 2451.97   201.9 2450.73   275.6 2451.55   299.1 2452.06   317.3 2450.85
   332.2 2452.15   339.3  2452.1     348 2452.81   360.7 2455.73   372.6 2456.69
   386.9 2460.83   403.5 2463.39   417.8 2464.44   454.1 2472.46   470.7 2477.12
#Mann= 7 ,-1 , 0
       0     .06       0    39.3     .12       0    60.9     .08       0
   115.7     .04       0   137.1     .12       0   275.6     .08       0
   339.3     .12       0
Bank Sta=115.7,137.1
XS Rating Curve= 0 ,0
Exp/Cntr(USF)=0,0
Exp/Cntr=0.5,0.3

Type RM Length L Ch R = 1 ,7654    ,343.9,376.9,327.7
XS GIS Cut Line= 4
     2044006.982      346397.263     2044188.149      346530.637
     2044230.384      346582.875     2044468.235      346709.581
#Sta/Elev= 30
       0  2486.4    17.5 2484.85    54.2 2479.68    66.4  2477.9    82.7 2474.44
   123.5 2468.77   127.5 2467.44   137.9 2460.64     149 2456.15   157.7 2451.44
   162.4 2450.08   188.6 2449.05   206.7    2450   234.5 2450.19   246.3 2449.59
     251 2447.95   264.1 2447.07   268.3 2447.94   272.4 2450.56   274.8 2450.78
   303.2 2450.63   336.4 2451.98   380.8 2454.59   406.2  2457.9   430.5 2463.84
   441.6 2468.93   451.1 2470.51   460.2 2475.46   521.5  2494.3   561.6 2509.66
#Mann= 6 ,-1 , 0
       0    .016       0   33.22     .12       0    69.9     .08       0
     251     .04       0   268.3     .08       0  356.76     .12       0
Bank Sta=251,268.3
XS Rating Curve= 0 ,0
Exp/Cntr=0.3,0.1

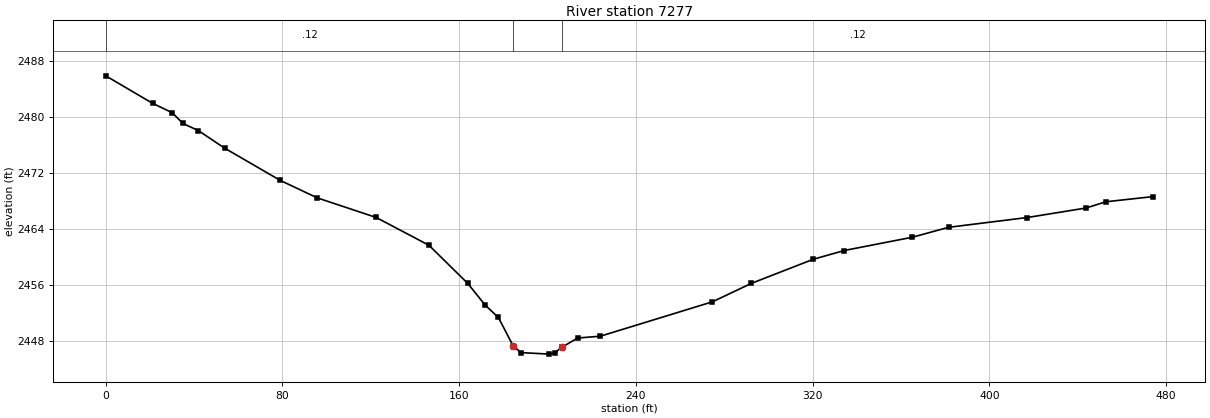
Type RM Length L Ch R = 1 ,7277    ,245.8,249,240.1
XS GIS Cut Line= 3
      2043822.48      346615.107     2044019.208      346814.057
     2044150.359      346957.435
#Sta/Elev= 30
       0 2485.83    21.2  2481.9    30.1 2480.56    34.9 2479.03    41.9 2478.01
    53.8  2475.5      79 2470.89    95.8 2468.39   122.4  2465.6   146.3 2461.63
   163.9 2456.17   171.8 2453.06   177.7 2451.33   184.5 2447.21     188  2446.3
   200.8 2446.08   203.2 2446.27   206.6 2447.08   213.6 2448.38   223.9 2448.64
   274.6 2453.55   292.3 2456.19   320.3 2459.63   334.3 2460.88   365.2 2462.78
   381.5 2464.19   417.1 2465.59   443.8 2466.95   452.7 2467.84   474.1 2468.58
#Mann= 3 ,-1 , 0
       0     .12       0   184.5     .04       0   206.6     .12       0
Bank Sta=184.5,206.6
XS Rating Curve= 0 ,0
Exp/Cntr=0.3,0.1