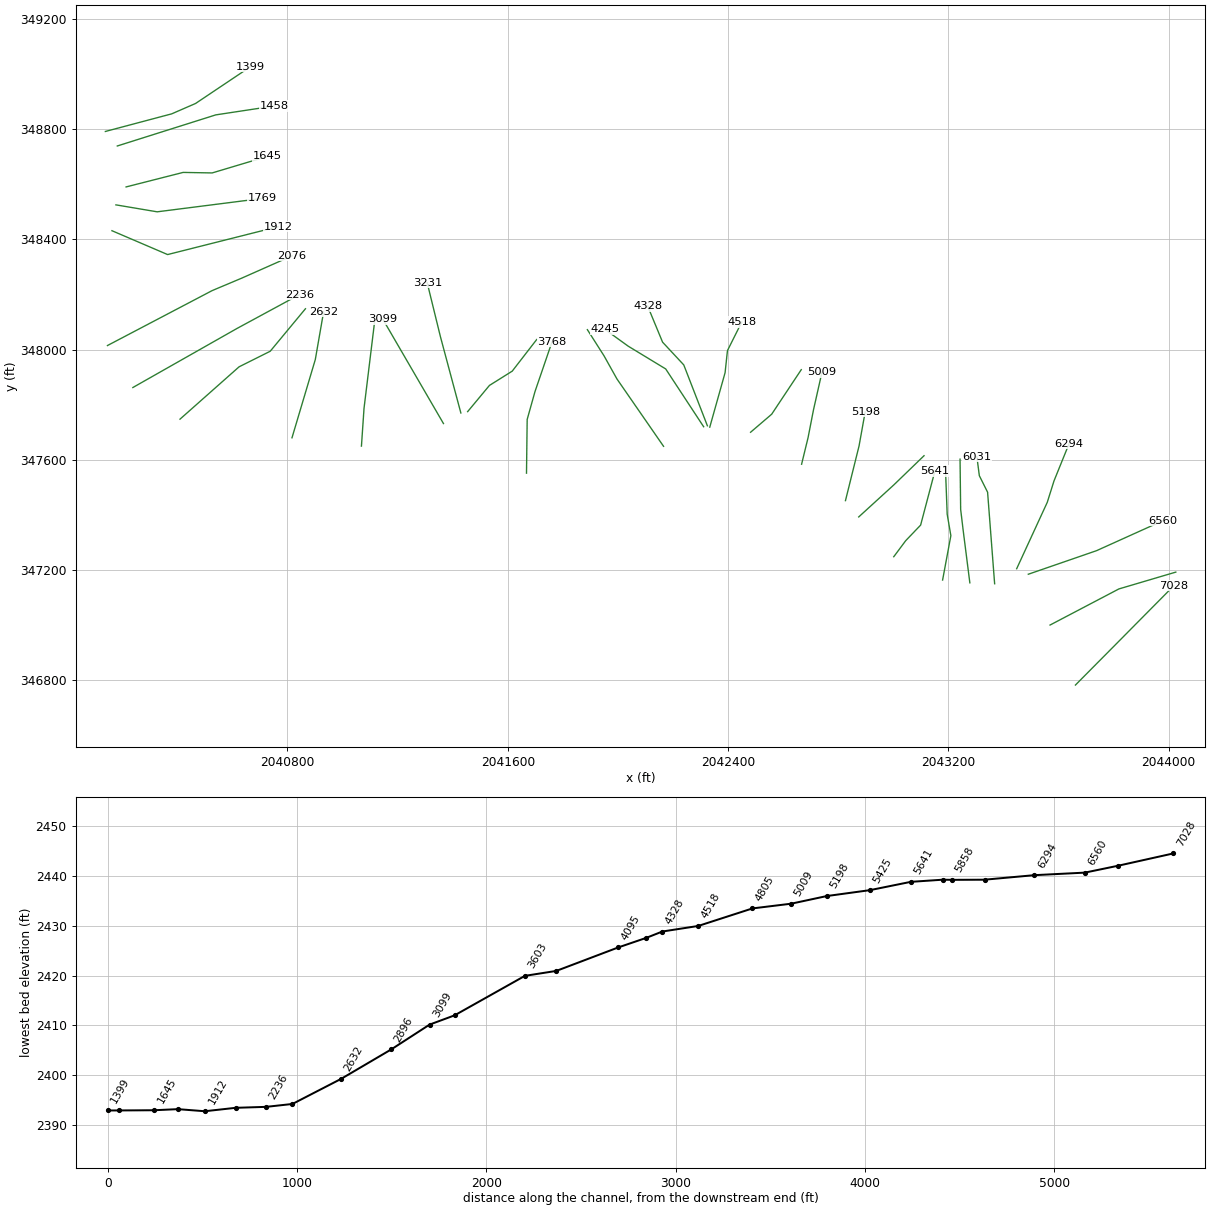
HEC-RAS study LTSEWELLCK.prj: LTSEWELLCK

--- LTSEWELLCK.g01 (geometry) --- (continued)

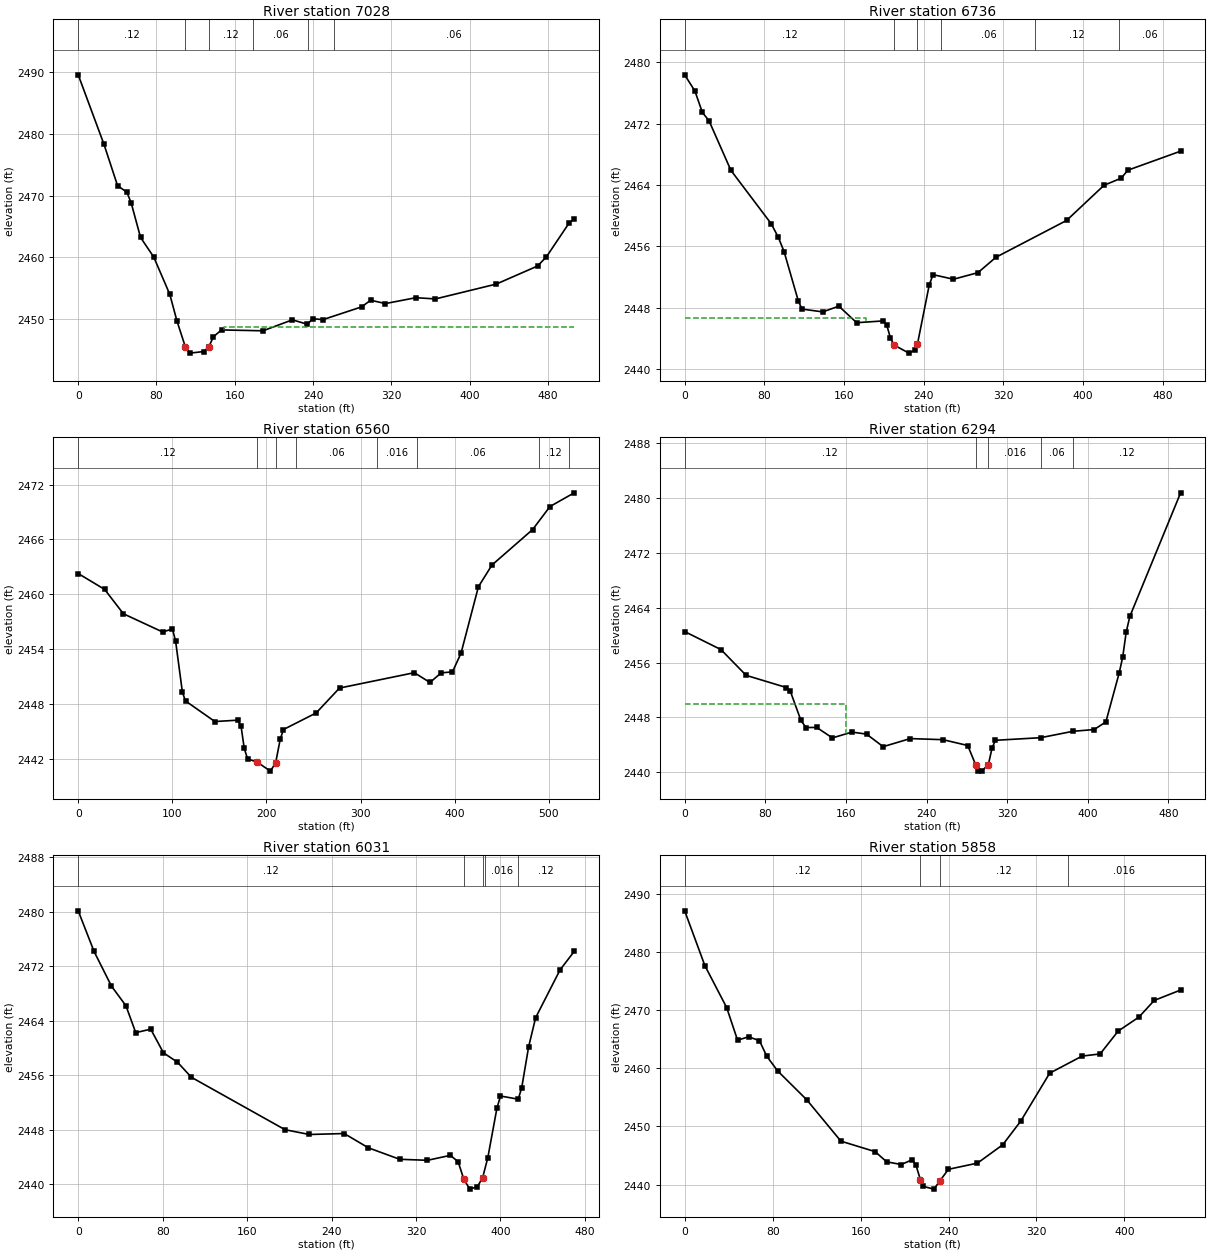
Type RM Length L Ch R = 1 ,7028    ,266.8,292.8,219.6
XS GIS Cut Line= 3
      2043661.32      346781.825     2043794.694      346916.311
     2044018.096      347141.936
#Sta/Elev= 30
       0 2489.51    26.4 2478.25    40.2  2471.6    49.7 2470.54    54.1 2468.83
    63.7 2463.23    77.2 2460.06    93.6 2454.03   100.9 2449.74   109.5 2445.54
   114.1 2444.53   128.4 2444.79   133.5 2445.55   138.2 2447.18   146.5 2448.28
   188.8 2448.14   218.9 2449.91   234.2  2449.2   239.8  2450.1   250.1 2449.94
   289.6    2452   298.9 2453.08     314 2452.54   345.1 2453.49   365.1 2453.29
   427.3 2455.69   469.5 2458.61   478.6  2460.1     502 2465.62   506.9 2466.17
#Mann= 6 ,-1 , 0
       0     .12       0   109.5     .04       0   133.5     .12       0
  178.58     .06       0  235.28     .12       0  261.72     .06       0
#XS Ineff= 2 , 0
                          148.56         2448.73
Permanent Ineff=
       F       F
Bank Sta=109.5,133.5
XS Rating Curve= 0 ,0
Exp/Cntr=0.3,0.1

Type RM Length L Ch R = 1 ,6736    ,176.8,175.5,168.4
XS GIS Cut Line= 3
     2043569.069       346999.67     2043819.146      347130.822
     2044025.876      347191.952
#Sta/Elev= 30
       0 2478.36    10.3 2476.24    17.7 2473.47    24.5 2472.35    46.4  2465.9
    86.9 2458.93      94 2457.17    99.8  2455.3     114 2448.91   117.7  2447.8
   138.7 2447.43   154.8 2448.18   172.7 2446.02   199.2 2446.25   202.9 2445.72
   206.6 2444.02   210.3  2443.1   225.2 2442.05   231.1 2442.43   233.72443.209
   245.6 2450.96   249.4 2452.29   269.9 2451.69   294.5 2452.55   312.6 2454.56
   383.5 2459.36   421.1 2463.95   438.2 2464.87   445.1 2465.92     498  2468.4
#Mann= 6 ,-1 , 0
       0     .12       0   210.3     .04       0   233.7     .12       0
  257.86     .06       0  352.14     .12       0  436.27     .06       0
#XS Ineff= 2 , 0
          182.31 2446.58
Permanent Ineff=
       F       F
Bank Sta=210.3,233.7
XS Rating Curve= 0 ,0
Exp/Cntr=0.3,0.1

Type RM Length L Ch R = 1 ,6560    ,230.7,266.4,303.2
XS GIS Cut Line= 3
     2043490.156      347184.171      2043738.01      347269.753
     2043979.195      347378.676
#Sta/Elev= 30
       0 2462.27    28.1 2460.53      48 2457.87    89.7 2455.88   100.1 2456.21
   103.5 2454.86   110.7 2449.29     114 2448.34   145.2 2446.09   169.5 2446.24
     173 2445.58   176.4 2443.16   179.9 2442.02   190.3 2441.64   204.2 2440.67
   209.82441.595   214.6 2444.15   218.1 2445.22   252.8 2447.03   277.6 2449.75
   357.1 2451.43   373.7 2450.36   385.6 2451.41   397.6 2451.52   406.7 2453.56
   425.2 2460.83   439.6  2463.2   482.8 2467.08   501.2 2469.59   526.9 2471.09
#Mann= 8 ,-1 , 0
       0     .12       0   190.3     .04       0   209.8     .12       0
  231.33     .06       0  317.73    .016       0  359.82     .06       0
  489.45     .12       0  521.86     .08       0
Bank Sta=190.3,209.8
XS Rating Curve= 0 ,0
Exp/Cntr=0.3,0.1

Type RM Length L Ch R = 1 ,6294    ,227.6,263.3,280.1
XS GIS Cut Line= 4
     2043447.921      347204.177     2043559.066      347445.363
     2043583.518      347523.165     2043637.979       347657.65
#Sta/Elev= 30
       0 2460.53      36  2457.9      61 2454.14     101 2452.36   104.7 2451.88
   115.4 2447.55   120.4 2446.52     131 2446.54   146.6 2445.01   166.1 2445.86
   180.5 2445.56     197 2443.73   223.9 2444.91   256.4 2444.75   280.9  2443.9
   288.8 2441.09   291.2 2440.19   294.6 2440.16   301.42441.104     305 2443.51
   308.4 2444.66   353.3 2445.04   385.2 2445.97   406.4 2446.23     418 2447.34
   431.2 2454.47   434.7 2456.79   438.2 2460.46   441.8 2462.74   492.2 2480.78
#Mann= 5 ,-1 , 0
       0     .12       0   288.8     .04       0   301.4    .016       0
   353.3     .06       0   385.2     .12       0
#XS Ineff= 2 , 0
             160    2450
Permanent Ineff=
       F       F
Bank Sta=288.8,301.4
XS Rating Curve= 0 ,0
Exp/Cntr=0.3,0.1

Type RM Length L Ch R = 1 ,6031    ,162.5,172.1,140.4
XS GIS Cut Line= 4
     2043367.896      347149.716     2043342.333      347482.041
     2043312.323      347542.059     2043303.432      347610.969
#Sta/Elev= 30
       0  2480.1      15 2474.14    31.5 2469.05    45.2 2466.17    54.5 2462.22
    68.7 2462.73    80.8 2459.25      94 2457.89   107.2 2455.67     196 2447.97
     219 2447.27     252 2447.41     275 2445.31   304.6 2443.63   330.9 2443.48
   352.7 2444.21     360 2443.26   365.3 2440.73     371 2439.25   378.3 2439.62
   383.2 2440.95   388.1 2443.87   396.7 2451.11   400.1 2452.92   416.9 2452.45
   420.2 2454.12   426.8 2460.17   433.4 2464.41   456.6 2471.45   469.9 2474.13
#Mann= 5 ,-1 , 0
       0     .12       0   365.3     .04       0   383.2     .12       0
  385.69    .016       0  416.92     .12       0
Bank Sta=365.3,383.2
XS Rating Curve= 0 ,0
Exp/Cntr=0.5,0.3

Type RM Length L Ch R = 1 ,5858    ,48.3,48.9,53.4
XS GIS Cut Line= 4
     2043277.868      347153.051     2043253.416      347345.332
     2043244.525      347419.799     2043242.302      347602.078
#Sta/Elev= 30
       0 2487.08    18.4 2477.64    38.2 2470.44    48.1 2464.83    58.1 2465.42
      68 2464.75    74.6  2462.1    84.5 2459.56     111 2454.59   142.1 2447.47
   173.2 2445.67   183.7 2443.92     197 2443.45   206.9 2444.27   210.2 2443.45
   214.4 2440.85   216.8  2439.7   226.7 2439.22   232.1 2440.63   239.9 2442.63
   266.3 2443.69   289.3 2446.85   305.7 2450.92     332 2459.16   361.5  2462.1
   377.9 2462.47   394.3  2466.4   413.2 2468.81   427.1 2471.67   451.1 2473.46
#Mann= 4 ,-1 , 0
       0     .12       0   214.4     .04       0   232.1     .12       0
  348.39    .016       0
Bank Sta=214.4,232.1
XS Rating Curve= 0 ,0
Exp/Cntr=0.5,0.3

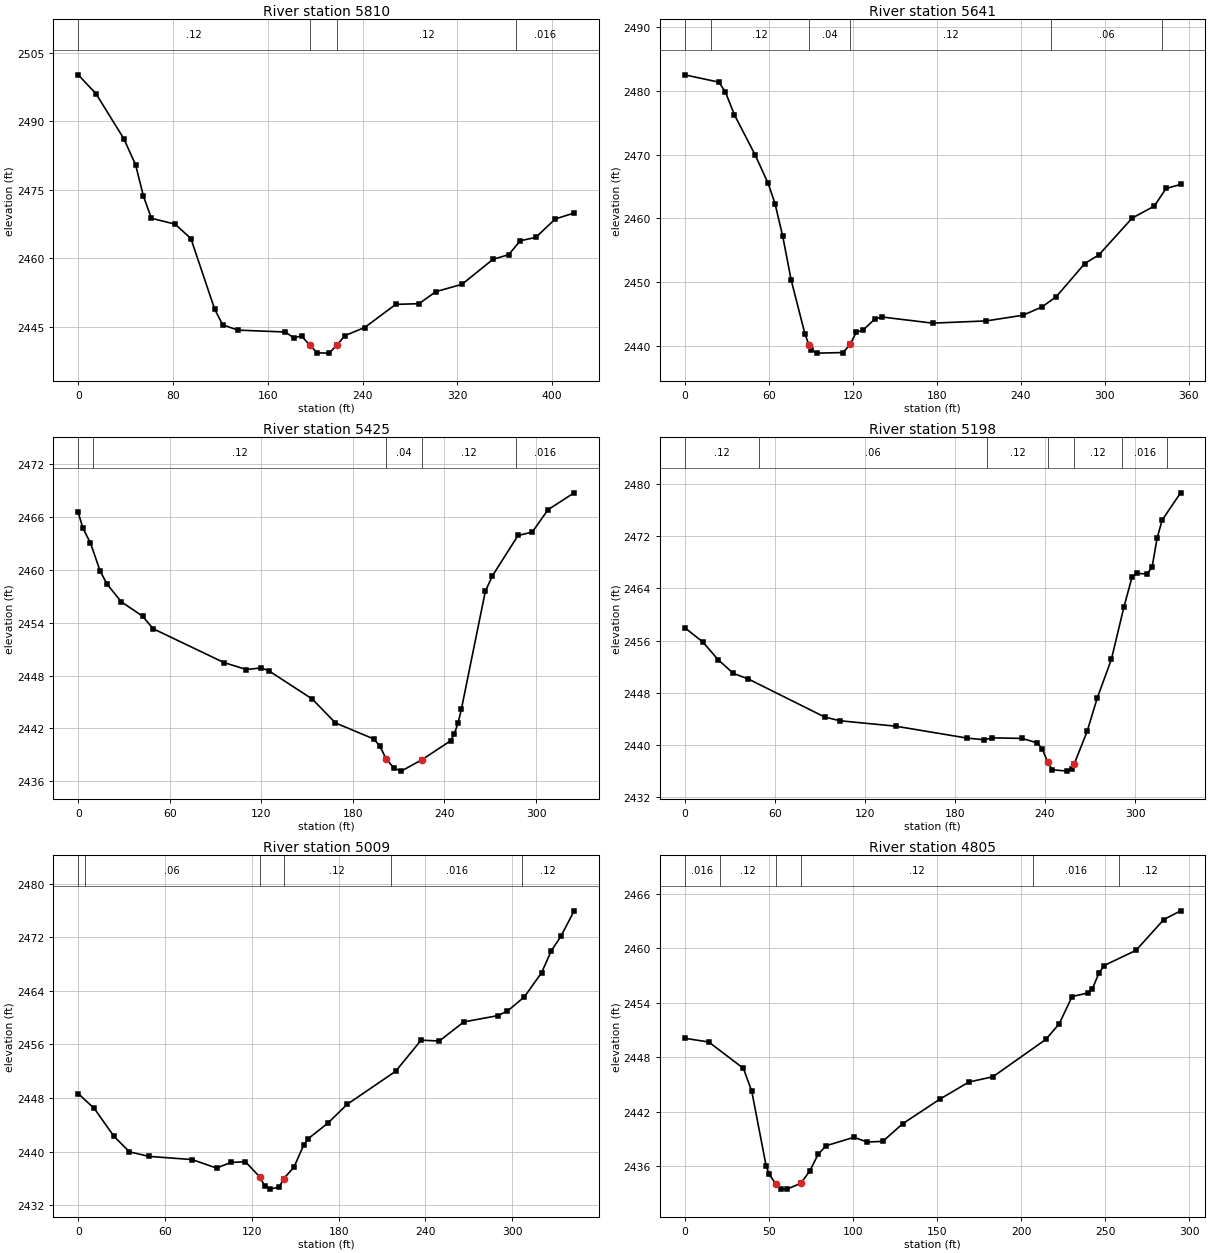
Type RM Length L Ch R = 1 ,5810    ,171.6,168.2,132.3
XS GIS Cut Line= 4
     2043178.949      347163.054     2043208.958      347324.214
     2043195.621      347402.016     2043188.952      347577.626
#Sta/Elev= 30
       0 2500.21      15 2496.07    38.4 2486.26    48.4 2480.52    55.1 2473.59
    61.8 2468.79    81.8  2467.5    95.1 2464.35   115.1 2448.94   121.8 2445.48
   134.6 2444.29   174.8 2443.88   181.8 2442.62   188.5 2442.99   195.5 2440.99
   201.8 2439.31   211.8 2439.25   218.5 2441.05   225.1 2443.09   241.8 2444.86
     268 2449.93   287.7 2450.08   301.8 2452.71   323.9 2454.32   350.1  2459.8
   363.3 2460.81   373.1 2463.86   386.2  2464.6   402.7 2468.64   418.6 2469.94
#Mann= 4 ,-1 , 0
       0     .12       0   195.5     .04       0   218.5     .12       0
  369.84    .016       0
Bank Sta=195.5,218.5
XS Rating Curve= 0 ,0
Exp/Cntr=0.5,0.3

Type RM Length L Ch R = 1 ,5641    ,213,216.3,214.9
XS GIS Cut Line= 4
     2043001.611      347247.771     2043044.834      347305.814
     2043099.171      347362.621     2043151.039      347558.978
#Sta/Elev= 30
       0 2482.53    24.4 2481.38    29.1 2479.83    35.5 2476.25    50.2    2470
    59.6 2465.48    64.5  2462.3      70 2457.18      76 2450.33    85.9 2441.81
    88.82440.058    90.5 2439.33    94.5 2438.82   113.1 2438.91   118.22440.209
   122.5  2442.1   127.3 2442.42   135.9  2444.2     141 2444.49     177 2443.53
   215.3 2443.88   241.5 2444.77   255.1 2446.07   265.3 2447.68   285.6 2452.88
   295.8 2454.26   319.5 2460.03   335.3 2461.91   343.7 2464.68   354.1 2465.31
#Mann= 6 ,-1 , 0
       0    .016       0   19.06     .12       0    88.8     .04       0
   118.2     .12       0  261.85     .06       0  340.62    .016       0
Bank Sta=88.8,118.2
XS Rating Curve= 0 ,0
Exp/Cntr=0.3,0.1

Type RM Length L Ch R = 1 ,5425    ,218.6,227.3,234
XS GIS Cut Line= 3
     2042874.411       347392.26     2043001.611      347508.345
     2043111.521      347614.551
#Sta/Elev= 30
       0  2466.5     3.1  2464.7       8 2463.05    14.3 2459.89    18.9 2458.36
    28.2 2456.37    42.2 2454.73    49.1 2453.31    95.5 2449.47   110.2 2448.68
   119.9 2448.86   124.8 2448.55   153.3 2445.34   168.6 2442.62   193.8 2440.79
   197.7 2439.98   201.8 2438.54     207 2437.48   211.7 2437.15   225.4 2438.46
     244 2440.59   246.5 2441.41     249 2442.65   251.1 2444.18   266.8 2457.56
   271.4  2459.3   288.2 2463.89   297.5 2464.27   307.9 2466.82     325 2468.73
#Mann= 5 ,-1 , 0
       0    .016       0    9.97     .12       0   201.8     .04       0
   225.4     .12       0  286.79    .016       0
Bank Sta=201.8,225.4
XS Rating Curve= 0 ,0
Exp/Cntr=0.3,0.1

Type RM Length L Ch R = 1 ,5198    ,191.6,188.7,187.3
XS GIS Cut Line= 3
     2042826.248      347451.538     2042875.646      347650.364
     2042897.875      347773.859
#Sta/Elev= 30
       0 2457.99    12.1 2455.79    22.2 2453.09    32.4 2450.97    42.5  2450.1
    93.2 2444.28   103.4  2443.7   140.5 2442.87   187.9 2441.05   199.6 2440.78
   204.8 2441.08   224.8 2440.99   234.8 2440.31   238.1 2439.42   241.9 2437.36
   244.8 2436.19   254.8 2435.97   258.1  2436.3   259.62437.118   268.1 2442.06
   274.8 2447.15   284.3 2453.15   292.7 2461.22   298.1  2465.8   301.4 2466.32
   308.1 2466.22   311.4  2467.3   314.8 2471.79   318.1  2474.5   330.4 2478.68
#Mann= 7 ,-1 , 0
       0     .12       0   49.27     .06       0  201.44     .12       0
   241.9     .04       0   259.6     .12       0  291.53    .016       0
  321.54     .12       0
Bank Sta=241.9,259.6
XS Rating Curve= 0 ,0
Exp/Cntr=0.3,0.1

Type RM Length L Ch R = 1 ,5009    ,194.3,204.7,173.3
XS GIS Cut Line= 4
      2042666.94      347583.677     2042690.404      347680.003
     2042710.163      347781.269     2042741.037      347918.348
#Sta/Elev= 30
       0 2448.67    11.1 2446.46    24.6 2442.34    35.4 2439.99      49 2439.31
    78.7 2438.84    95.6 2437.57   105.6 2438.42   115.6  2438.5   125.5 2436.25
     129 2434.85   132.4 2434.43     139 2434.75     1422435.986   149.1 2437.69
   155.8 2440.97   159.1 2441.97   172.5 2444.26   185.8 2447.06   219.4    2452
     237 2456.64   249.6 2456.52   266.5 2459.36     290  2460.3   296.7 2460.98
   308.4  2463.1   320.3 2466.71     327 2469.96   333.7 2472.15   342.8 2475.93
#Mann= 6 ,-1 , 0
       0    .016       0    4.41     .06       0   125.5     .04       0
     142     .12       0  216.11    .016       0  306.94     .12       0
Bank Sta=125.5,142
XS Rating Curve= 0 ,0
Exp/Cntr=0.5,0.3

Type RM Length L Ch R = 1 ,4805    ,280.3,286.3,294.3
XS GIS Cut Line= 3
     2042481.698      347699.762     2042558.264      347765.214
     2042665.705      347926.993
#Sta/Elev= 30
       0  2450.1    14.3 2449.69    34.9 2446.79    39.9 2444.25    48.4 2436.07
    50.1 2435.16    54.12434.071      57 2433.53    60.8 2433.48    69.12434.124
    74.3 2435.46    79.4 2437.33    84.1 2438.26   100.6 2439.19   108.5 2438.67
   117.8 2438.74   129.6 2440.68   151.8  2443.4     169 2445.28   183.3 2445.86
   214.8 2449.98   222.7 2451.69   230.4  2454.7     240  2455.1   242.4 2455.54
   246.3 2457.27   249.4 2458.11   268.4 2459.79   284.9 2463.18   294.9 2464.14
#Mann= 6 ,-1 , 0
       0    .016       0   21.16     .12       0    54.1     .04       0
    69.1     .12       0  207.06    .016       0  258.36     .12       0
Bank Sta=54.1,69.1
XS Rating Curve= 0 ,0
Exp/Cntr=0.5,0.3

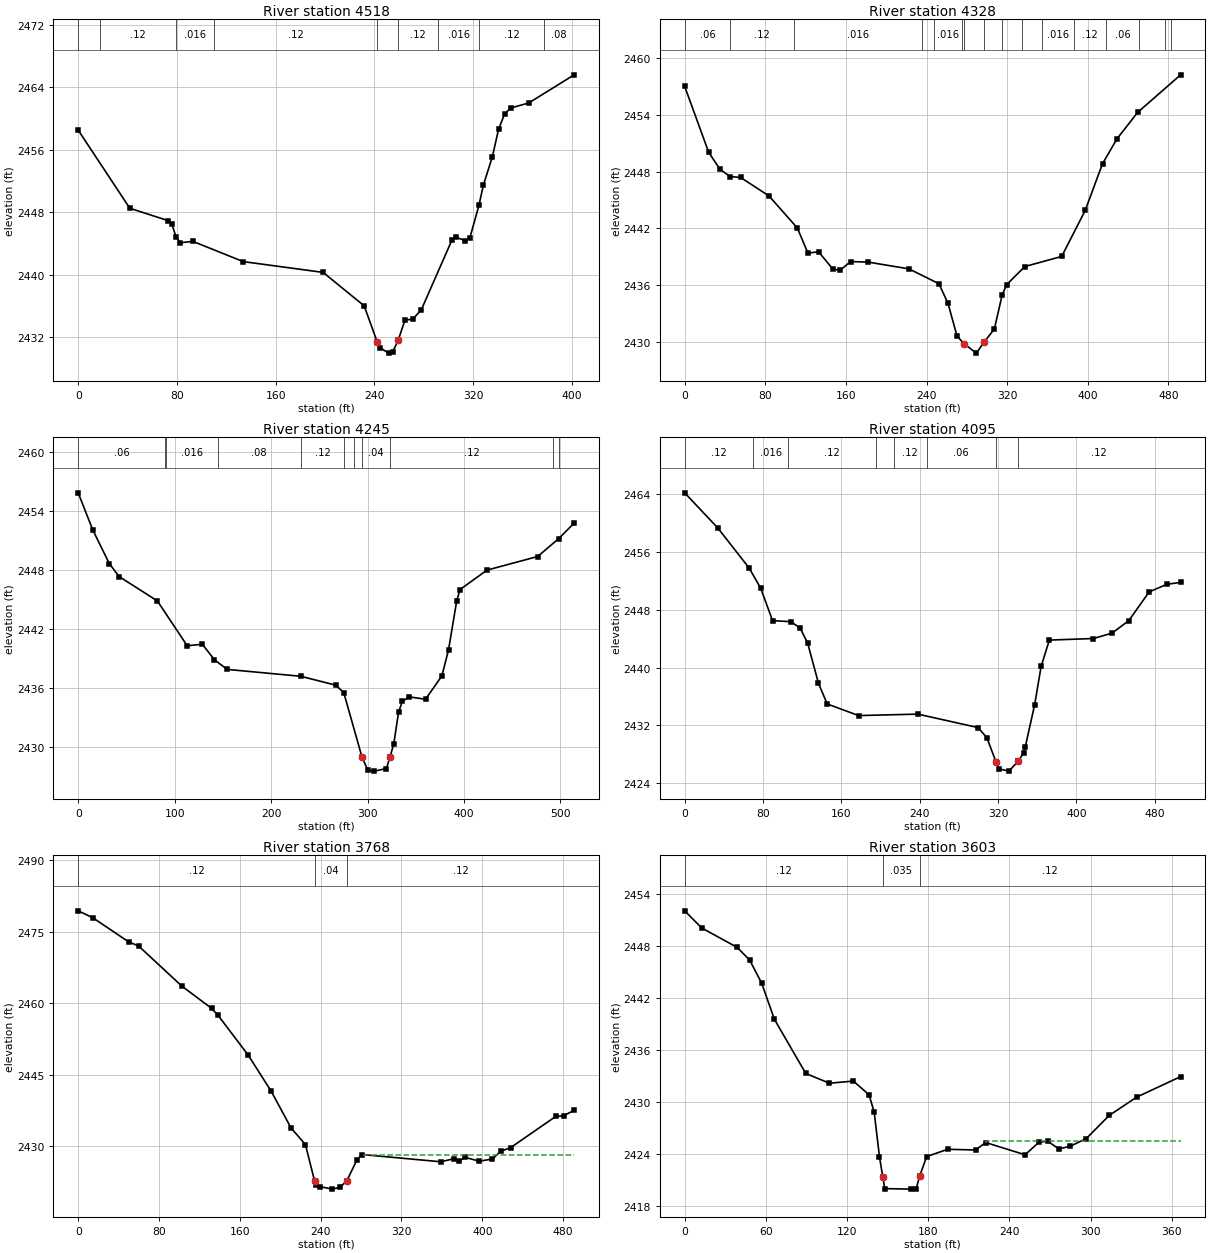
Type RM Length L Ch R = 1 ,4518    ,181,189.7,202
XS GIS Cut Line= 4
     2042333.504      347718.286     2042389.076      347915.878
     2042397.721       347996.15     2042449.589      348099.885
#Sta/Elev= 30
       0 2458.49    41.8  2448.5    72.5 2446.93    75.9 2446.47    79.3 2444.83
    82.7 2444.08    92.9 2444.26   133.8 2441.67   198.5 2440.29   231.8 2436.01
   242.4 2431.37     245 2430.62   251.6 2429.96   254.9 2430.11   259.3 2431.58
   264.8 2434.16   271.4 2434.33   278.2 2435.54   302.8 2444.38   306.4 2444.78
   313.8 2444.34   317.5 2444.73   324.8 2448.86   328.5 2451.51   335.7 2455.07
   340.7 2458.59   345.6 2460.55   350.5 2461.32   365.2 2461.97     402 2465.57
#Mann= 9 ,-1 , 0
       0     .06       0   18.03     .12       0   79.39    .016       0
  110.08     .12       0   242.4     .04       0   259.3     .12       0
  291.95    .016       0  324.97     .12       0  377.64     .08       0
Bank Sta=242.4,259.3
XS Rating Curve= 0 ,0
Exp/Cntr=0.5,0.3

Type RM Length L Ch R = 1 ,4328    ,78.2,83.9,90
XS GIS Cut Line= 4
     2042324.859      347723.226     2042239.106      347944.243
     2042162.132      348026.888     2042107.845      348158.148
#Sta/Elev= 30
       0 2456.98    23.8 2450.03    34.9 2448.25      45 2447.47    55.5 2447.37
    83.6 2445.43   111.8 2442.04   122.3 2439.39   132.9 2439.53     147 2437.71
   154.1 2437.57   164.6  2438.5   182.2 2438.44   222.5 2437.73   252.3 2436.16
   261.3 2434.09   270.2 2430.65   277.1 2429.85   289.3 2428.84   297.1 2429.99
   307.3  2431.4   315.1 2435.01   319.6 2436.08   337.4 2437.97   374.1 2439.04
   397.4 2443.89   414.6 2448.82   428.9 2451.44   449.4 2454.23   492.1  2458.2
#Mann= 16 ,-1 , 0
       0     .06       0      45     .12       0  108.36    .016       0
  235.09     .12       0  247.57    .016       0  274.91     .12       0
   277.1     .04       0   297.1     .08       0  315.28     .12       0
  334.25     .08       0  354.47    .016       0  386.43     .12       0
   418.4     .06       0  450.36     .12       0  476.48     .06       0
  482.32     .12       0
Bank Sta=277.1,297.1
XS Rating Curve= 0 ,0
Exp/Cntr=0.3,0.1

Type RM Length L Ch R = 1 ,4245    ,156.9,149.4,139.2
XS GIS Cut Line= 4
     2042311.218      347719.804     2042173.475      347929.658
     2042037.354      348012.304     2041953.088      348073.072
#Sta/Elev= 30
       0 2455.81    14.9 2452.09    32.3 2448.62    42.4 2447.32    82.1 2444.84
     113  2440.3   128.7 2440.45   141.3 2438.87   154.4  2437.9   230.8  2437.2
     267  2436.3   275.3 2435.55   294.3 2428.98   300.4 2427.65   306.9 2427.58
   319.5 2427.84   323.3 2429.02   327.2 2430.36   332.2 2433.59   336.2 2434.68
   343.4 2435.11   360.1 2434.87   377.1 2437.25     384 2439.91   392.4 2444.84
   395.9    2446   423.8 2447.97   476.4 2449.35   498.1 2451.16   514.2 2452.74
#Mann= 11 ,-1 , 0
       0     .06       0   89.61     .12       0   90.63    .016       0
  144.46     .08       0  230.93     .12       0  275.57    .016       0
  286.28     .12       0   294.3     .04       0   323.3     .12       0
  492.74    .016       0   498.1     .12       0
Bank Sta=294.3,323.3
XS Rating Curve= 0 ,0
Exp/Cntr=0.3,0.1

Type RM Length L Ch R = 1 ,4095    ,337.7,326.8,313.2
XS GIS Cut Line= 4
     2042165.671      347648.689     2041996.483      347893.209
     2041949.555      347977.185     2041889.042      348072.276
#Sta/Elev= 30
       0 2464.21    33.8 2459.34    65.8 2453.79    77.6 2450.99    89.7  2446.5
   108.3 2446.35   117.8 2445.49   125.6 2443.36   136.6  2437.8   145.5 2434.95
   177.5 2433.34     238 2433.54   299.4 2431.68   308.4  2430.3   317.82426.928
   321.1 2425.95     331 2425.64   340.4    2427   340.4 2427.01     346 2428.16
   347.6 2428.93   357.3 2434.86   363.9 2440.16   372.3  2443.8   417.2 2444.02
   436.2 2444.76   453.3 2446.48   474.2 2450.48   492.2 2451.53   506.3  2451.8
#Mann= 8 ,-1 , 0
       0     .12       0   69.82    .016       0  105.73     .12       0
  194.98     .06       0  213.49     .12       0   246.9     .06       0
   317.8     .04       0   340.4     .12       0
Bank Sta=317.8,340.4
XS Rating Curve= 0 ,0
Exp/Cntr=0.3,0.1

Type RM Length L Ch R = 1 ,3768    ,174.6,165.7,152.6
XS GIS Cut Line= 4
     2041667.987      347551.128     2041670.457       347746.25
      2041698.86      347847.516     2041760.608      348027.818
#Sta/Elev= 30
       0 2479.39    14.4 2477.94    49.9 2472.87    59.8    2472   102.4 2463.61
     132  2458.9   138.5 2457.41   168.1 2449.13     191  2441.5   210.6  2433.8
   224.9 2430.29  234.03  2422.6   235.2 2421.85     239 2421.47   251.6 2420.93
     259 2421.31   265.8 2422.65     276 2427.12   280.9  2428.2   358.8 2426.68
   371.9 2427.31     377 2426.82   383.1  2427.6     397  2426.8   409.9 2427.25
   418.4  2428.9   428.2 2429.67   472.6 2436.19   480.4 2436.34   490.9 2437.48
#Mann= 3 , 0 , 0
       0     .12       0  234.03     .04       0   265.8     .12       0
#XS Ineff= 2 , 0
                          282.07         2428.18
Permanent Ineff=
       F       F
Bank Sta=234.03,265.8
XS Rating Curve= 0 ,0
Exp/Cntr=0.3,0.1

Type RM Length L Ch R = 1 ,3603    ,364.7,371.4,378.1
XS GIS Cut Line= 4
     2041454.341      347774.654     2041533.377      347869.745
     2041616.119      347921.613     2041705.035      348036.463
#Sta/Elev= 30
       0 2452.08    12.7 2450.09    38.8 2447.86      48  2446.4    56.9 2443.73
    66.3 2439.56    89.5  2433.3     107 2432.17   124.7 2432.42   136.3 2430.83
   140.1 2428.81     144 2423.67   146.42421.366   147.9    2420   167.2 2419.94
   171.1 2419.98  173.65 2421.42   178.9  2423.7   194.4 2424.54     215 2424.46
   222.5 2425.32   251.6 2423.91   261.8 2425.34   268.2 2425.49   276.5 2424.59
   284.8 2424.88   296.9 2425.78   313.8 2428.45   334.3 2430.58   366.6 2432.93
#Mann= 3 ,-1 , 0
       0     .12       0   146.4    .035       0  173.65     .12       0
#XS Ineff= 2 , 0
                          223.04         2425.53
Permanent Ineff=
       F       F
Bank Sta=146.4,173.65
XS Rating Curve= 0 ,0
Exp/Cntr=0.3,0.1

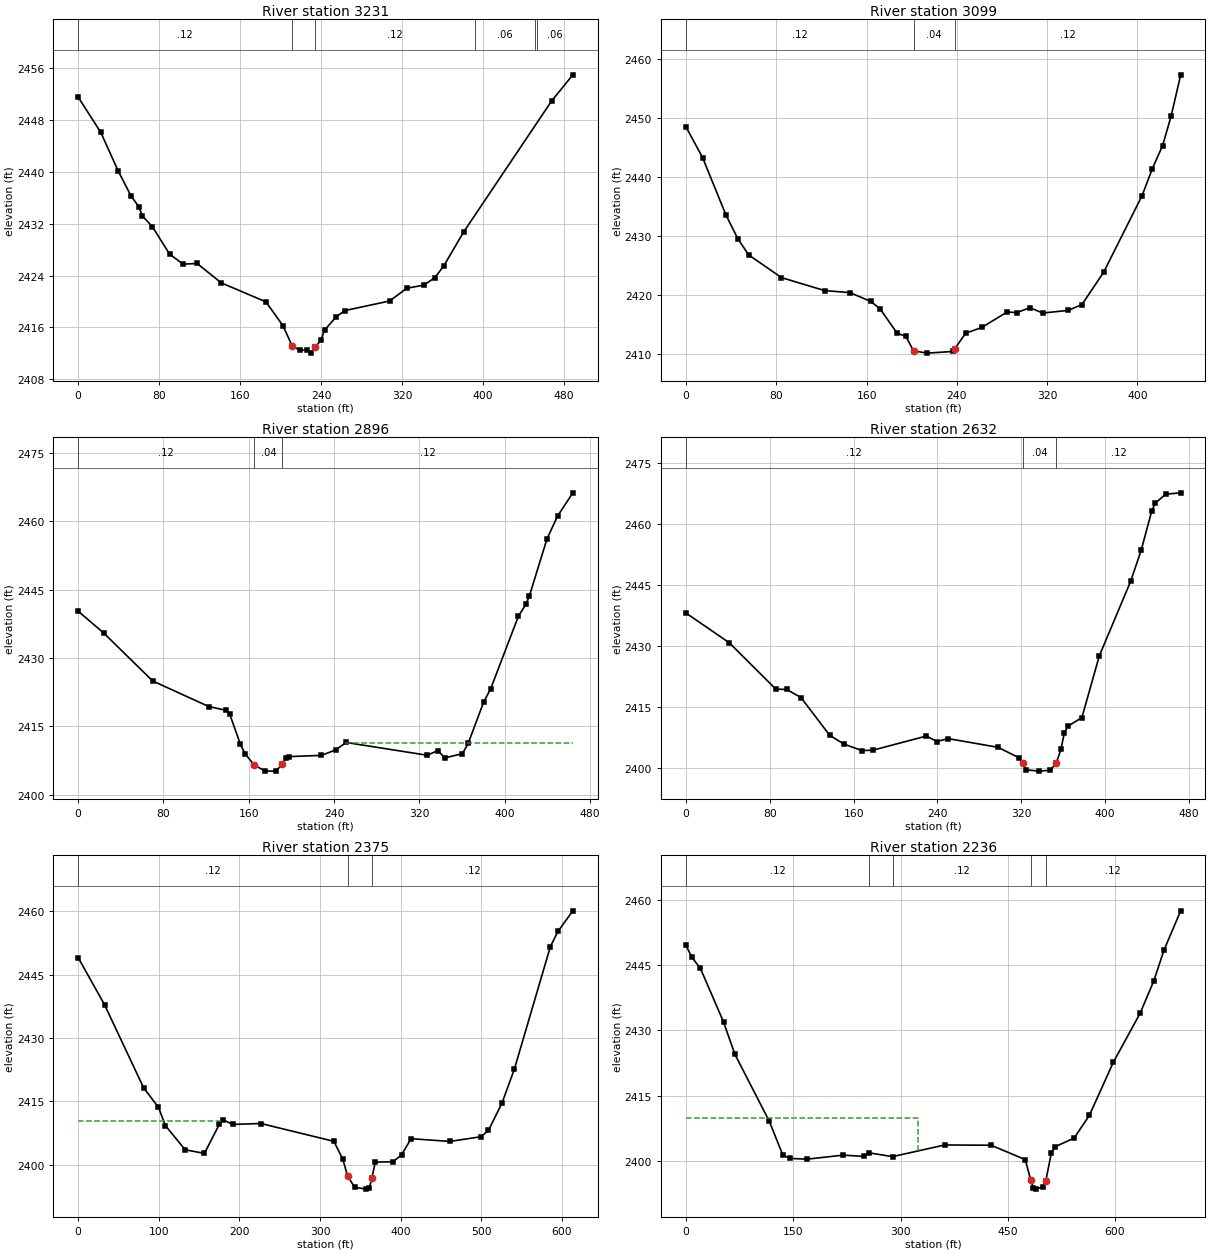
Type RM Length L Ch R = 1 ,3231    ,128.2,132.1,137.3
XS GIS Cut Line= 3
     2041429.642      347769.714     2041355.545      348046.342
     2041307.382      348242.699
#Sta/Elev= 30
       0 2451.58    22.4  2446.1    39.4  2440.2    52.3 2436.27    59.8 2434.66
    63.5 2433.18    73.3 2431.56    90.3 2427.31   103.7 2425.76   117.5 2425.86
   141.3 2422.87   185.4 2419.94   202.4 2416.23   211.52413.073   219.4 2412.43
   226.2 2412.52   229.6 2412.01   234.32412.949   239.8 2414.02   243.4 2415.58
   255.1 2417.65   263.5 2418.59   307.6 2420.06   324.5 2422.03   341.4 2422.52
   352.4 2423.67   361.3 2425.54   380.8 2430.74   467.6 2450.96   488.6 2455.01
#Mann= 6 ,-1 , 0
       0     .12       0   211.5     .04       0   234.3     .12       0
  392.23     .06       0  451.16     .12       0  453.06     .06       0
Bank Sta=211.5,234.3
XS Rating Curve= 0 ,0
Exp/Cntr=0.3,0.1

Type RM Length L Ch R = 1 ,3099    ,211.8,202.9,192.9
XS GIS Cut Line= 2
2041366.47766614347731.330527268 2041146.2851939348110.350356548
#Sta/Elev= 30
       0 2448.52    14.8 2443.27    35.3 2433.62      46 2429.52    55.6  2426.8
    84.6 2422.96   122.8 2420.76   145.3 2420.41   163.6 2418.93   171.9 2417.68
     187 2413.54   194.8 2412.99   201.6 2410.54   213.6 2410.15   236.4 2410.43
     238 2410.85   247.7 2413.51     262  2414.5   284.5 2417.12   293.3 2417.03
   304.7 2417.86     316 2416.95   338.8  2417.4   350.8 2418.39     370 2423.85
   404.1 2436.86   413.2 2441.44   422.3 2445.36   429.9  2450.4   438.3 2457.35
#Mann= 3 , 0 , 0
       0     .12       0   201.6     .04       0     238     .12       0
Bank Sta=201.6,238
XS Rating Curve= 0 ,0
Exp/Cntr(USF)=0,0
Exp/Cntr=0.3,0.1

Type RM Length L Ch R = 1 ,2896    ,254.7,264.6,257.8
XS GIS Cut Line= 3
     2041068.625      347649.452     2041078.036      347786.857
     2041117.563      348110.605
#Sta/Elev= 30
       0 2440.27    23.8 2435.52    69.9 2424.95   122.5 2419.34     139  2418.5
   142.2 2417.63   152.2 2411.01   156.6 2408.94   165.3 2406.46   175.3 2405.18
   185.2 2405.16   191.6 2406.66   195.1 2408.05   197.9 2408.35   228.2 2408.62
   241.4 2409.81   251.3 2411.45   327.3 2408.65   337.3 2409.66   343.9 2408.07
   360.4 2408.99   365.8 2411.26   380.2 2420.28   386.8 2423.21   412.9  2439.2
   419.9 2441.76   423.2 2443.66   439.7 2456.17   449.6 2461.16   463.9 2466.26
#Mann= 3 ,-1 , 0
       0     .12       0   165.3     .04       0   191.6     .12       0
#XS Ineff= 2 , 0
                             250          2411.4
Permanent Ineff=
       F       F
Bank Sta=165.3,191.6
XS Rating Curve= 0 ,0
Exp/Cntr=0.3,0.1

Type RM Length L Ch R = 1 ,2632    ,290.5,257.1,217.1
XS GIS Cut Line= 3
     2040816.402      347679.568     2040901.104      347963.789
      2040931.22      348136.956
#Sta/Elev= 30
       0 2438.12    41.3 2430.82    85.8  2419.4    96.1 2419.34   109.8 2417.34
   137.2 2408.06   150.9 2405.88     168 2404.31   178.3 2404.39   229.6 2407.88
   239.6 2406.52   250.2 2407.25     298  2405.1     318 2402.53   321.3 2401.16
   324.7 2399.56   337.5 2399.25     348 2399.47   353.6 2401.28     358 2404.64
   361.3 2408.72   364.6 2410.27     378 2412.43   394.6 2427.58   424.6 2445.97
   434.6 2453.57   444.6 2463.15   447.9 2465.11   457.9 2467.34   472.3 2467.68
#Mann= 3 ,-1 , 0
       0     .12       0   321.3     .04       0   353.6     .12       0
#XS Ineff= 2 , 0
           225.7  2407.6
Permanent Ineff=
       F       F
Bank Sta=321.3,353.6
XS Rating Curve= 0 ,0
Exp/Cntr=0.3,0.1

Type RM Length L Ch R = 1 ,2375    ,129.4,138.6,136.7
XS GIS Cut Line= 4
     2040409.835      347747.329     2040624.412      347937.437
     2040737.348      347993.905     2040865.341       348148.25
#Sta/Elev= 30
       0 2449.06    32.8 2437.86    81.2 2418.21    99.6 2413.59   108.3 2409.23
   132.8 2403.52   156.6 2402.68   175.2 2409.59   180.2 2410.59   191.6 2409.54
   226.7 2409.75   317.2 2405.53   328.2 2401.28   334.2  2397.3   342.8 2394.67
   357.1 2394.21   361.2 2394.55   364.4 2396.95   368.5  2400.6   390.5  2400.7
   401.1 2402.33   412.9 2406.16   460.9 2405.51   499.5 2406.62   508.8  2408.1
   525.5 2414.53   540.9 2422.58   585.7 2451.68     595 2455.25   613.5 2460.13
#Mann= 3 ,-1 , 0
       0     .12       0   334.2     .04       0   364.4     .12       0
#XS Ineff= 2 , 0
             178  2410.4
Permanent Ineff=
       F       F
Bank Sta=334.2,364.4
XS Rating Curve= 0 ,0
Exp/Cntr=0.3,0.1

Type RM Length L Ch R = 1 ,2236    ,176.4,160.5,154.6
XS GIS Cut Line= 3
      2040238.55      347862.147     2040616.883      348076.724
     2040842.754      348199.071
#Sta/Elev= 30
       0 2449.49       8 2446.82    20.1 2444.24    52.5 2431.95    68.2  2424.6
   116.4 2409.21   135.5 2401.42   145.2 2400.67   169.4  2400.5   219.8 2401.42
   248.7 2401.13   255.9 2401.95   288.8 2401.08   361.8 2403.75   426.8 2403.69
   474.5 2400.39     482 2395.75   485.7 2393.98   489.7 2393.63   499.4  2394.2
   503.22395.545   510.8 2401.83   515.6  2403.3   542.9 2405.35   564.1 2410.53
   597.7 2422.74     635 2433.92   654.3 2441.39   668.5 2448.44   691.8 2457.42
#Mann= 5 ,-1 , 0
       0     .12       0   255.9    .016       0   288.8     .12       0
     482     .04       0   503.2     .12       0
#XS Ineff= 2 , 0
             325    2410
Permanent Ineff=
       F       F
Bank Sta=482,503.2
XS Rating Curve= 0 ,0
Exp/Cntr=0.5,0.3

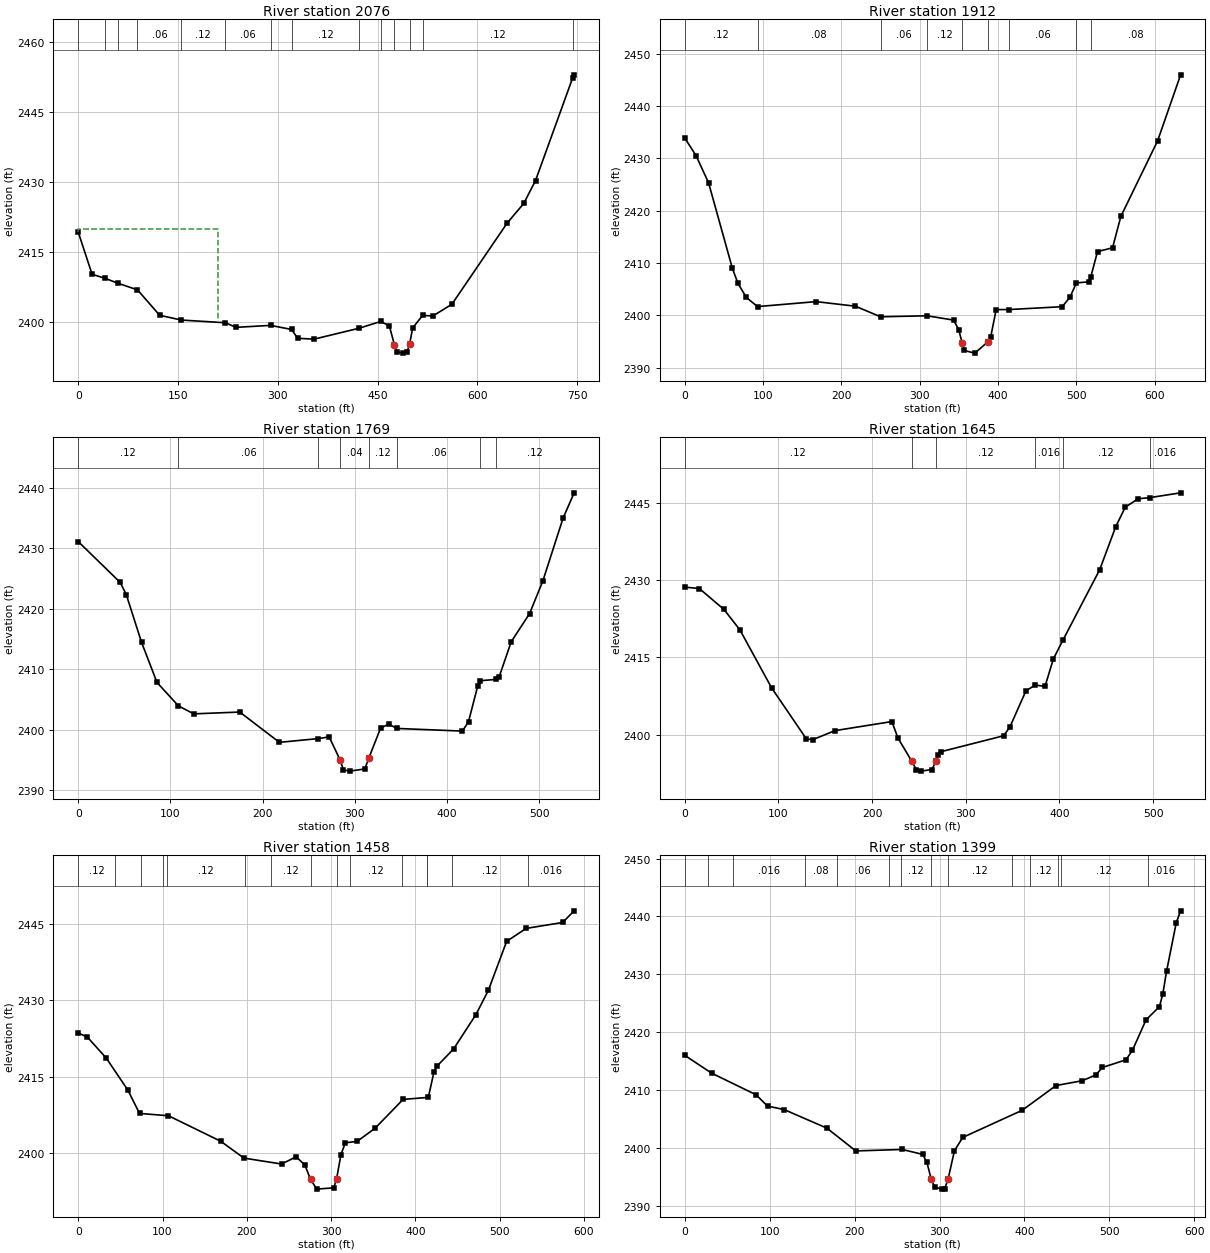
Type RM Length L Ch R = 1 ,2076    ,187.9,163.5,153.7
XS GIS Cut Line= 4
     2040146.319       348014.61     2040526.535      348214.129
     2040633.824      348259.303     2040816.402       348340.24
#Sta/Elev= 30
       0 2419.38    20.8 2410.33    40.9 2409.43    59.4 2408.41    89.1 2406.99
   122.4 2401.55     155 2400.52   221.1 2399.95   237.3 2398.96   289.1 2399.38
   320.7 2398.51   329.9 2396.61   354.7 2396.44   422.5 2398.78   454.8 2400.22
   467.7 2399.27   475.2 2395.28   479.7 2393.72   487.7 2393.44     494 2393.63
   498.2 2395.36   502.7 2398.83   517.8 2401.52   533.1 2401.39   561.7  2403.9
   644.8 2421.29   669.7 2425.48   687.4 2430.38   743.1 2452.32   745.5 2453.03
#Mann= 14 ,-1 , 0
       0     .12       0    40.9     .08       0    59.4     .12       0
    89.1     .06       0     155     .12       0   221.1     .06       0
   289.1    .016       0   320.7     .12       0   422.5    .016       0
   454.8     .12       0   475.2     .04       0   498.2    .016       0
   517.8     .12       0   743.1     .06       0
#XS Ineff= 2 , 0
             210    2420
Permanent Ineff=
       F       F
Bank Sta=475.2,498.2
XS Rating Curve= 0 ,0
Exp/Cntr=0.5,0.3

Type RM Length L Ch R = 1 ,1912    ,155,143,135.3
XS GIS Cut Line= 3
 2040162.6384941348431.6147832712040364.78240305348344.981679436
2040765.46050829 348446.05363391
#Sta/Elev= 30
       0 2433.91    14.5 2430.52    30.5 2425.33    60.9 2408.96      68  2406.1
    78.7  2403.4      93 2401.65   167.9  2402.6     218 2401.72   250.1  2399.7
   309.4 2399.89   343.3 2399.07     350 2397.22   354.2 2394.71   356.8 2393.26
   370.4 2392.75   387.2 2394.91   390.6 2395.76   397.7 2401.08   413.7 2401.08
     482 2401.63     492 2403.45   500.1 2406.18   515.8 2406.38   518.4 2407.26
   527.1 2412.17   546.3 2412.89   556.9  2418.9   603.8 2433.34   633.2 2445.97
#Mann= 9 ,-1 , 0
       0     .12       0      93     .08       0   250.1     .06       0
   309.4     .12       0   354.2     .04       0   387.2     .12       0
   413.7     .06       0   500.1    .016       0   518.4     .08       0
Bank Sta=354.2,387.2
XS Rating Curve= 0 ,0
Exp/Cntr(USF)=0,0
Exp/Cntr=0.5,0.3

Type RM Length L Ch R = 1 ,1769    ,132.1,124.4,116.6
XS GIS Cut Line= 3
2040177.07734474348525.4673124262040326.88042012348500.199323808
2040709.50996206348548.930444715
#Sta/Elev= 30
       0 2431.13    45.5 2424.38    52.1 2422.36    68.7 2414.45    85.4 2407.83
   108.7 2403.95   125.3 2402.64   175.1 2402.94   218.1 2397.93   260.3 2398.55
     272 2398.83   283.8 2395.05   287.5 2393.38   294.1 2393.17   310.7 2393.53
   315.1 2395.36   327.8 2400.29   336.6 2400.94   345.4 2400.23   416.5 2399.79
   423.1 2401.36     433  2407.2     436 2408.13   452.9 2408.33   456.2 2408.72
   469.4 2414.57   489.3 2419.22   503.8 2424.68   525.6 2435.01   537.6 2439.19
#Mann= 8 ,-1 , 0
       0     .12       0   108.7     .06       0   260.3     .12       0
   283.8     .04       0   315.1     .12       0   345.4     .06       0
     436    .016       0   452.9     .12       0
Bank Sta=283.8,315.1
XS Rating Curve= 0 ,0
Exp/Cntr(USF)=0,0
Exp/Cntr=0.3,0.1

Type RM Length L Ch R = 1 ,1645    ,168.1,186.6,197.5
XS GIS Cut Line= 4
     2040214.081       348590.58     2040421.129      348643.283
     2040526.535      348641.401     2040727.936      348701.633
#Sta/Elev= 30
       0 2428.62    15.6 2428.35    41.9  2424.3      59 2420.32    92.7 2409.11
   129.9 2399.19   136.7 2399.05   160.4  2400.8   221.1 2402.56   227.7 2399.34
   242.5 2394.82   247.4 2393.16   252.4 2392.95   263.8 2393.26   268.3 2394.91
   270.3 2396.11   273.6 2396.72   340.3  2399.8     347 2401.47   364.2 2408.51
     374 2409.63   384.6 2409.38   393.5 2414.71   403.6 2418.31   442.9 2431.98
     460 2440.31   470.2 2444.11   483.9 2445.75   496.1 2445.96   529.3  2446.9
#Mann= 6 ,-1 , 0
       0     .12       0   242.5     .04       0   268.3     .12       0
     374    .016       0   403.6     .12       0   496.1    .016       0
Bank Sta=242.5,268.3
XS Rating Curve= 0 ,0
Exp/Cntr=0.5,0.3

Type RM Length L Ch R = 1 ,1458    ,52.4,59,62.1
XS GIS Cut Line= 3
     2040182.082      348739.278     2040539.711      348852.214
     2040750.523      348884.212
#Sta/Elev= 30
       0 2423.57    10.8 2422.78    33.4 2418.62      59 2412.33    72.7 2407.78
   107.1 2407.32   169.1 2402.31   196.6    2399   241.3 2397.84   258.5 2399.26
   268.8 2397.66   275.7 2394.82   282.9 2392.91   303.2 2393.17   306.5 2394.93
   311.7 2399.71   316.9 2402.02   330.8 2402.28   352.3 2404.89   385.4 2410.53
   415.3 2410.93   421.9 2415.84   425.2    2417   445.2 2420.42   471.7 2427.17
   486.5 2431.94   508.2 2441.57   531.4 2444.12   574.6 2445.28   588.3 2447.57
#Mann= 15 ,-1 , 0
       0     .12       0   43.34     .06       0   74.31     .12       0
  100.07     .08       0  105.29     .12       0  198.17    .016       0
  229.19     .12       0   275.7     .04       0   306.5    .016       0
  322.11     .12       0  383.74    .016       0  413.62     .12       0
  413.79    .016       0  443.49     .12       0  533.12    .016       0
Bank Sta=275.7,306.5
XS Rating Curve= 0 ,0
Exp/Cntr=0.5,0.3

Type RM Length L Ch R = 1 ,1399    ,279.5,298.2,313.4
XS GIS Cut Line= 4
      2040138.79      348791.981     2040379.719      348855.978
     2040466.303      348893.623     2040665.822      349027.263
#Sta/Elev= 30
       0 2416.02    31.7 2412.94      84  2409.2    97.5 2407.25   117.1 2406.64
   167.5 2403.43   201.4  2399.5   256.1 2399.75   280.2  2398.9   285.2 2397.51
   290.2 2394.61   294.5 2393.25   302.6  2392.9   306.1 2392.98   310.1 2394.65
   317.6 2399.56   327.4 2401.84   397.3 2406.52   437.2  2410.8   468.1 2411.63
   483.9 2412.63   491.8 2413.92   519.4 2415.24     527 2416.85   543.1 2422.15
   558.9 2424.43   562.9 2426.67   567.2  2430.5   578.7 2438.95   583.8 2440.98
#Mann= 14 ,-1 , 0
       0    .016       0   27.14     .06       0   56.99    .016       0
   142.2     .08       0  179.24     .06       0  240.36    .016       0
  254.42     .12       0   290.2     .04       0   310.1     .12       0
  385.88     .06       0  406.86     .12       0  438.97     .06       0
  442.41     .12       0  545.12    .016       0
Bank Sta=290.2,310.1
XS Rating Curve= 0 ,0
Exp/Cntr=0.5,0.3