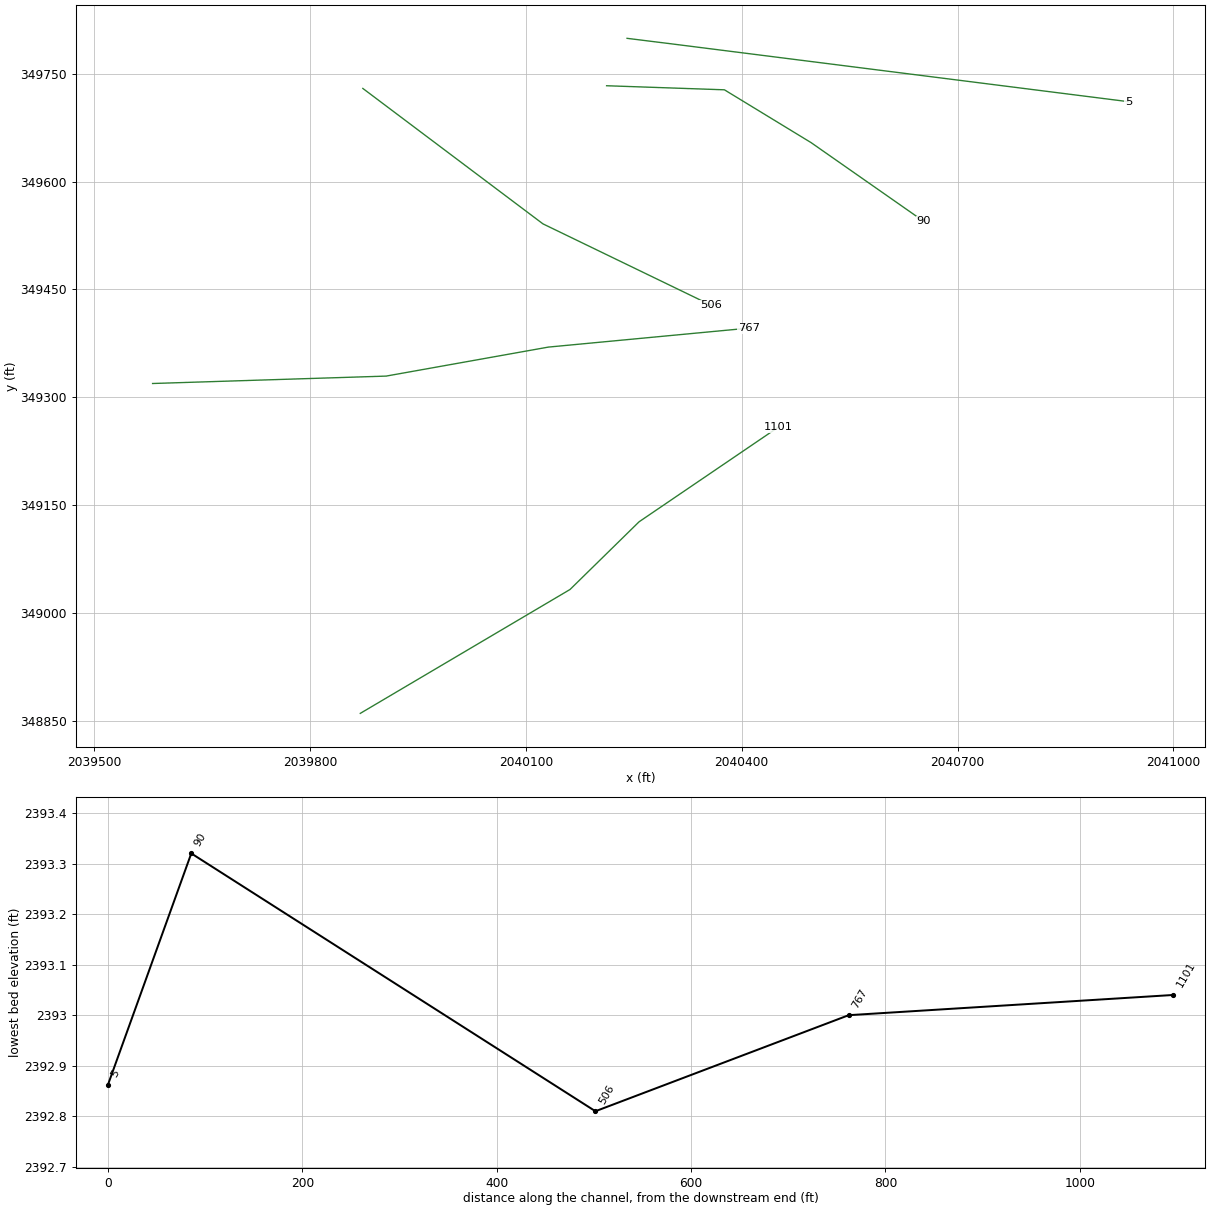
HEC-RAS study LTSEWELLCK.prj: LTSEWELLCK

--- LTSEWELLCK.g01 (geometry) --- (continued)

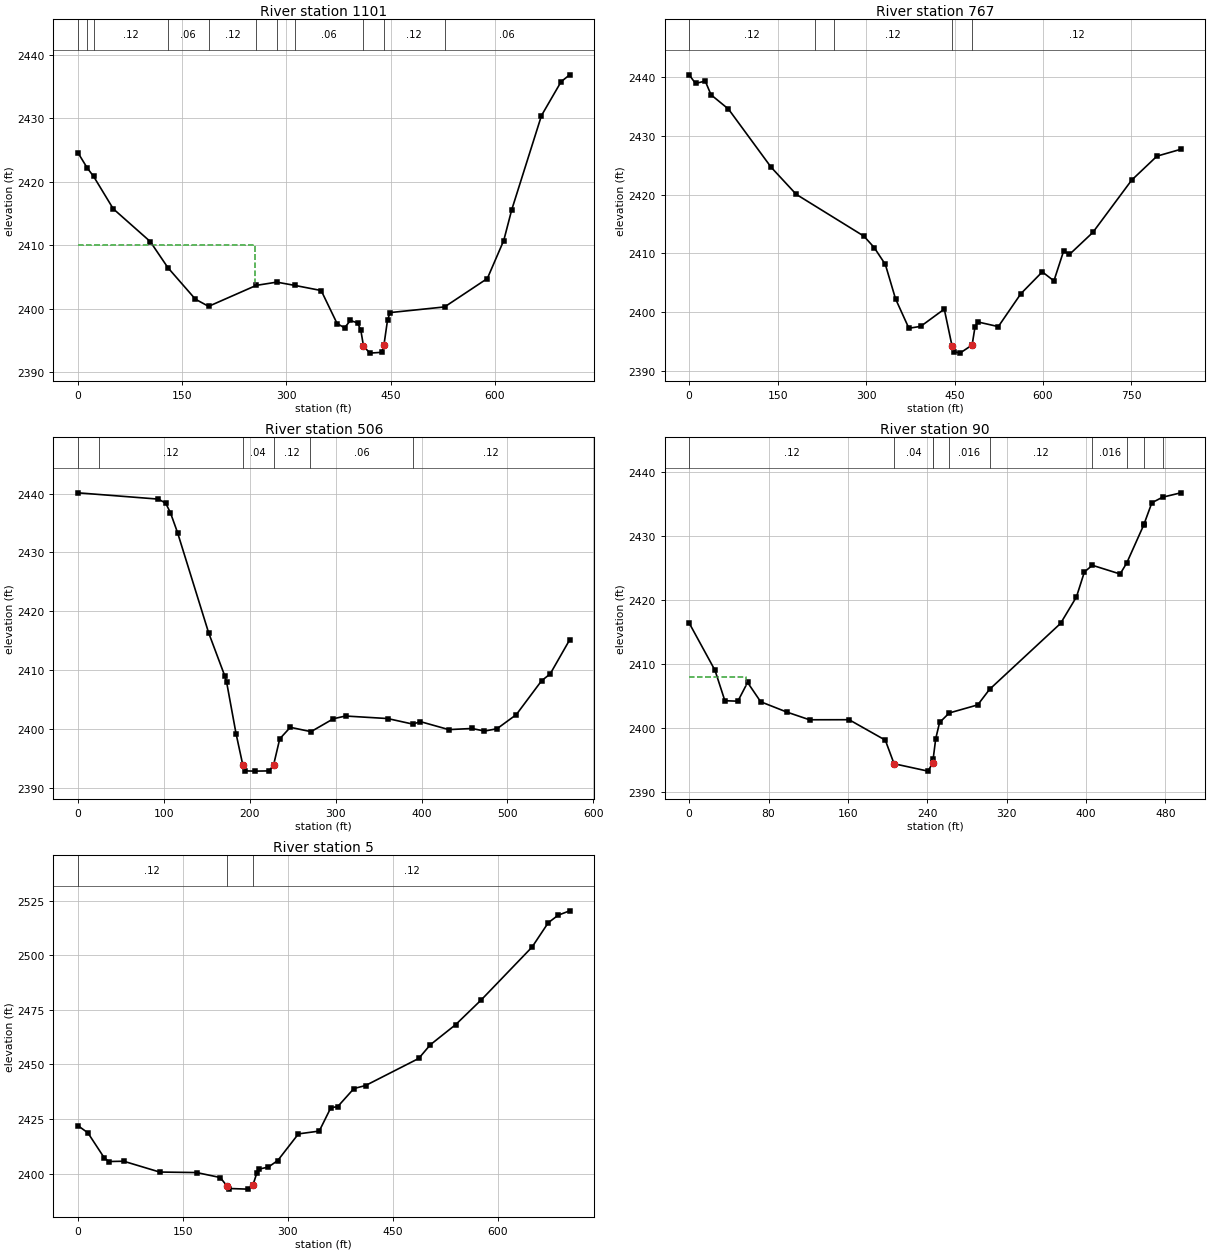
Type RM Length L Ch R = 1 ,1101    ,371,334.1,298.5
XS GIS Cut Line= 4
2039869.81197355348860.693716876     2040161.377       349032.91
     2040257.373      349127.023     2040451.245      349258.781
#Sta/Elev= 30
       0 2424.56    13.3 2422.17    22.5 2420.84    50.7 2415.75   103.9  2410.6
   129.4 2406.48   168.9 2401.53   187.9  2400.4   256.5  2403.7     286 2404.21
   312.3 2403.69   349.9 2402.89   372.8  2397.7   383.5 2397.02     392 2398.18
   402.2 2397.79   406.9 2396.68   410.8 2394.15   419.9 2393.04   437.2 2393.17
   440.32394.368   445.4 2398.26   449.1 2399.42   527.5 2400.31     589 2404.78
   612.6 2410.76   624.1  2415.6   666.9 2430.42   695.2 2435.76   707.5 2436.83
#Mann= 11 ,-1 , 0
       0     .12       0    13.3     .06       0    22.5     .12       0
   129.4     .06       0   187.9     .12       0   256.5     .04       0
     286     .12       0   312.3     .06       0   410.8     .04       0
   440.3     .12       0   527.5     .06       0
#XS Ineff= 2 , 0
             255    2410
Permanent Ineff=
       F       F
Bank Sta=410.8,440.3
XS Rating Curve= 0 ,0
Exp/Cntr=0.3,0.1

Type RM Length L Ch R = 1 ,767     ,281.3,260.6,187.9
XS GIS Cut Line= 4
2039581.13261964349319.2137345092039905.72358349349329.514381374
     2040131.261      349369.834     2040409.835      349396.185
#Sta/Elev= 30
       0 2440.43    10.8 2438.96    27.3 2439.37    37.1 2437.03    66.7 2434.59
     139 2424.68   181.5 2420.07   296.4 2412.93   313.7    2411   332.7 2408.11
   349.9 2402.27   372.6 2397.24   392.6 2397.56   432.6  2400.5   445.72394.247
   449.3 2393.25   459.2    2393   479.8 2394.38   484.6 2397.39   489.3 2398.32
   524.2 2397.52   562.5 2403.13   598.8 2406.85   618.5 2405.31     635 2410.41
   644.9 2409.82   684.5 2413.57   750.4 2422.49   793.2 2426.57   833.7 2427.74
#Mann= 5 ,-1 , 0
       0     .12       0     213     .04       0   246.1     .12       0
   445.7     .04       0   479.8     .12       0
#XS Ineff= 2 , 0
          199.04 2400.45
Permanent Ineff=
       F       F
Bank Sta=445.7,479.8
XS Rating Curve= 0 ,0
Exp/Cntr=0.3,0.1

Type RM Length L Ch R = 1 ,506     ,387.5,415.8,374.2
XS GIS Cut Line= 3
     2039873.392      349729.345     2040123.732      349541.119
     2040357.132      349428.184
#Sta/Elev= 30
       0 2440.13    93.6 2439.06   102.1 2438.37   107.6 2436.75   115.9 2433.37
   152.1 2416.33   170.9    2409   173.1  2407.9     184  2399.2     192 2393.78
   194.9 2392.85   206.2 2392.81   222.4 2392.85   227.7 2393.84   234.9  2398.3
   247.2 2400.26   271.3 2399.52   297.4 2401.72   311.5 2402.18   360.5 2401.75
     390  2400.8   398.6 2401.23   431.7 2399.87   458.8 2400.06   473.3 2399.62
   487.9 2400.02   510.3 2402.41   539.8 2408.18   549.8 2409.34   572.5 2415.14
#Mann= 6 ,-1 , 0
       0     .06       0   24.54     .12       0     192     .04       0
   227.7     .12       0  270.28     .06       0  389.61     .12       0
Bank Sta=192,227.7
XS Rating Curve= 0 ,0
Exp/Cntr=0.3,0.1

Type RM Length L Ch R = 1 ,90      ,59.1,85.8,98.1
XS GIS Cut Line= 4
     2040212.198      349733.109     2040375.955      349727.462
     2040496.419      349654.054     2040652.646      349544.884
#Sta/Elev= 30
       0 2416.43    26.1 2409.03      36  2404.3    49.1 2404.23    58.9 2407.15
    72.1 2404.14    98.3 2402.54   121.3 2401.33   161.2 2401.34   197.7 2398.15
   206.52394.471   240.7 2393.32   245.4 2394.57   245.92395.195   248.5 2398.39
   252.4 2400.91   262.1 2402.39   290.8 2403.65   302.7 2406.07   374.3 2416.36
   390.3 2420.49   398.3 2424.38   406.3 2425.43   434.3 2424.07     441 2425.79
   458.3 2431.78   458.3  2431.8   466.3 2435.18   477.1 2436.05   495.5 2436.73
#Mann= 10 ,-1 , 0
       0     .12       0   206.5     .04       0   245.4     .04       0
   245.9     .12       0   262.1    .016       0   302.7     .12       0
   406.3    .016       0     441     .12       0   458.3    .016       0
   477.1     .12       0
#XS Ineff= 2 , 0
           57.07 2407.96
Permanent Ineff=
       F       F
Bank Sta=206.5,245.4
XS Rating Curve= 0 ,0
Exp/Cntr=0.3,0.1

Type RM Length L Ch R = 1 ,5       ,,,
XS GIS Cut Line= 4
     2040240.653      349799.006     2040301.557      349791.442
     2040762.762      349733.077 2040937.9647054349710.905284817
#Sta/Elev= 30
       02421.932  14.1592418.636  37.3012407.301  43.9132405.505  65.3332405.642
 116.6622400.691 169.5742400.453 203.3022398.182 212.5652394.439 215.8722393.147
 242.3282392.862 250.2712394.918 255.5562400.176 259.077 2402.05 272.0912402.969
 285.4972405.951 315.0822418.168 344.8452419.451  361.382430.142 371.3012430.685
  394.452438.954 410.9852440.312 487.0462452.732 503.5812458.982 539.9582468.255
 576.6212479.619 649.089 2503.77 672.2382514.911 686.4192518.366 702.855 2520.36
#Mann= 3 , 0 , 0
       0     .12       0 212.565     .04       0 250.271     .12       0
Bank Sta=212.565,250.271
XS Rating Curve= 0 ,0
Exp/Cntr(USF)=0,0
Exp/Cntr=0.3,0.1
LCMann Table=0

Chan Stop Cuts=-1
Use User Specified Reach Order=0
Composite Channel Slope=5